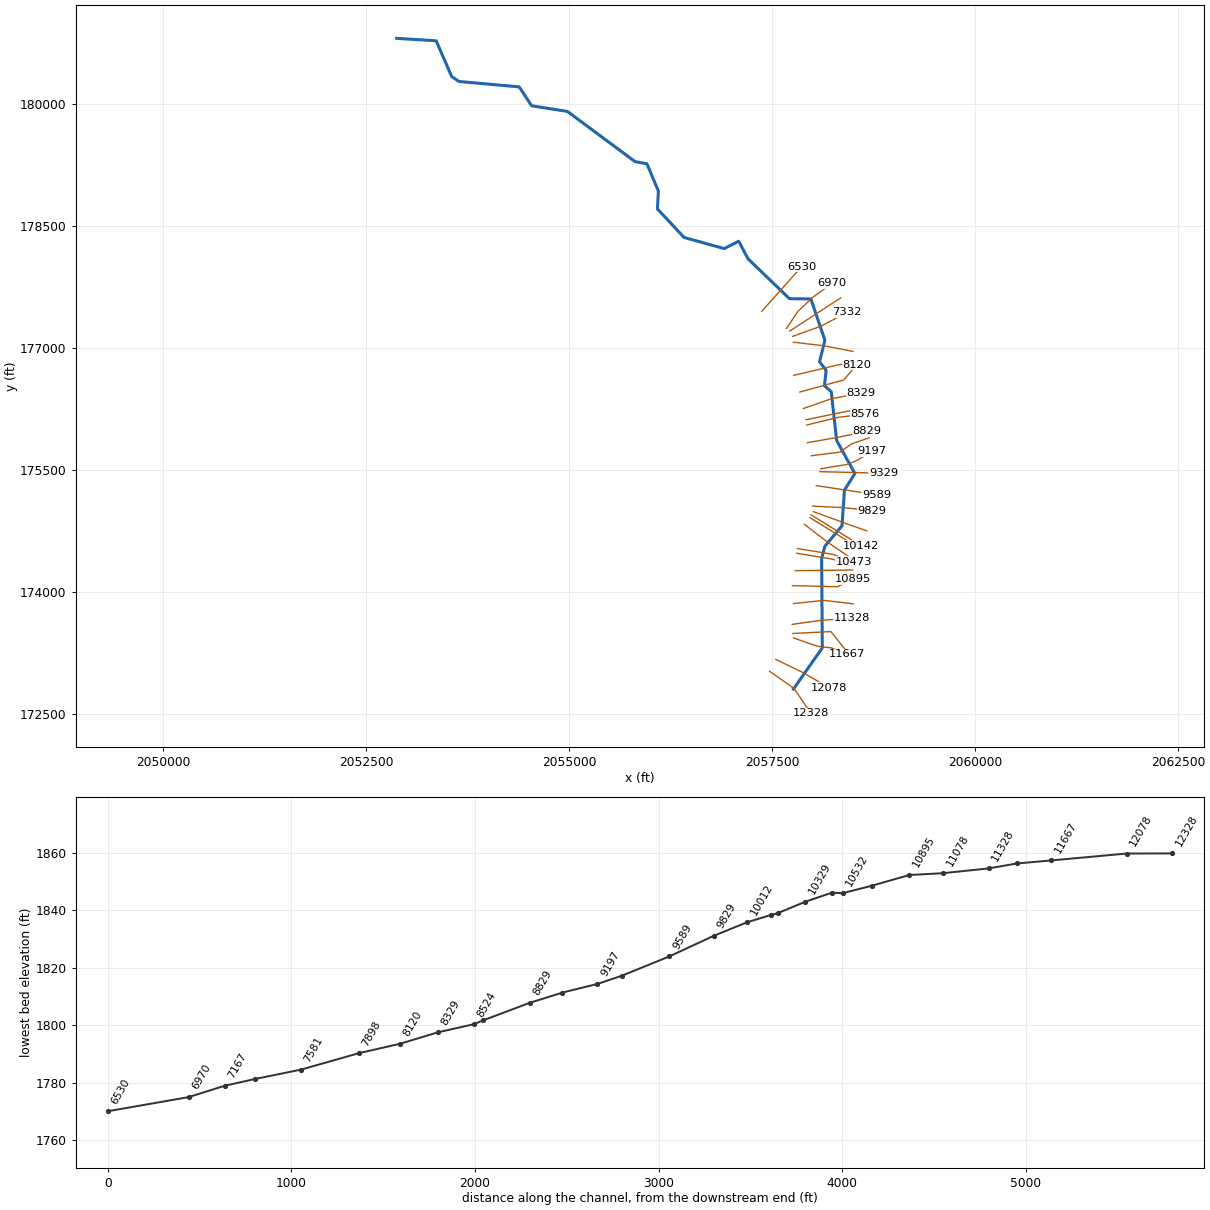
--- BLLKCK.prj (project) ---

Proj Title=BLLKCK
Current Plan=p01
Default Exp/Contr=0,0
English Units
Geom File=g01
Flow File=f01
Plan File=p01
Background Map Layer=Inundation Boundary (01pct Value_0)
Background Map Layer=Inundation Boundary (01pct Value_0)
Background Map Layer=Inundation Boundary (01pct Value_0)
BEGIN DESCRIPTION:
Stream Name: Blue Lick Creek
Flood Zone: Approximate
Monroe County, West Virginia
HEC-RAS Version: 5.0.7
Vertical Datum: NAVD88
Projection: NAD 1983 StatePlane West Virginia S FIPS 4702 (US Feet)
LiDAR: 2016, 1-meter
Land Use: 2016 NLCD
Hydrology Method:
Regression.
Model Notes:
END DESCRIPTION:
DSS File=dss
DSS Export Rating Curves= 0
DSS Export Rating Curve Sorted= 0
DSS Export Volume Flow Curves= 0
DXF OffsetX= 0
DXF OffsetY= 0
DXF ScaleX= 0
DXF ScaleY= 0

--- BLLKCK.p01 (plan) ---

Plan Title=Floodplain
Program Version=5.07
Short Identifier=Floodplain
Geom File=g01
Flow File=f01
Subcritical Flow
K Sum by GR= 0
Std Step Tol= 0.01
Critical Tol= 0.01
Num of Std Step Trials= 20
Max Error Tol= 0.3
Flow Tol Ratio= 0.001
Split Flow NTrial= 30
Split Flow Tol= 0.02
Split Flow Ratio= 0.02
Log Output Level= 0
Friction Slope Method= 1
Unsteady Friction Slope Method= 2
Unsteady Bridges Friction Slope Method= 1
Parabolic Critical Depth
Global Vel Dist= 0 , 0 , 0
Global Log Level= 0
CheckData=True
Encroach Param=-1 ,0,0, 0
Computation Interval=0.1SEC
Output Interval=1MIN
Instantaneous Interval=Max Profile
Mapping Interval=1HOUR
Computation Time Step Use Courant=        0
Computation Time Step Use Time Series=    0
Computation Time Step Count To Double=0
Computation Time Step Max Doubling=0
Computation Time Step Max Halving=0
Computation Time Step Residence Courant=0
Run HTab= 0
Run UNet= 0
Run Sediment= 0
Run PostProcess= 0
Run WQNet= 0
Run RASMapper=-1
UNET Theta= 0
UNET Theta Warmup= 0
UNET ZTol= 0
UNET ZSATol= 0
UNET MxIter= 0
UNET Max Iter WO Improvement= 0
UNET MaxInSteps= 0
UNET DtIC= 0
UNET DtMin= 0
UNET MaxCRTS= 0
UNET WFStab= 0
UNET SFStab= 0
UNET WFX= 1
UNET SFX= 1
UNET 1D Methodology=Finite Difference
UNET DSS MLevel= 1
UNET Pardiso=0
UNET DZMax Abort= 0
UNET Use Existing IB Tables= 0
UNET Froude Reduction=False
UNET Froude Limit= 0
UNET Froude Power= 0
UNET D1 Cores= 0
UNET D2 Coriolis=0
UNET D2 Cores= 0
UNET D2 Theta= 1
UNET D2 Theta Warmup= 1
UNET D2 Z Tol= 0.01
UNET D2 Volume Tol= 0.01
UNET D2 Max Iterations= 20
UNET D2 Equation= 0
UNET D2 RampUpFraction=0.1
UNET D2 TimeSlices= 1
UNET D2 BCVolumeCheck=0
UNET D1D2 MaxIter= 0
UNET D1D2 ZTol=0.01
UNET D1D2 QTol=0.1
UNET D1D2 MinQTol=1
DSS File=dss
Write IC File= 0
Write IC File at Fixed DateTime=0
Write IC File at Sim End=0
Echo Input=False
Echo Parameters=False
Echo Output=False
Write Detailed= 0
HDF Write Warmup=0
HDF Write Time Slices=0
HDF Flush=0
HDF Face Node Velocities=0
HDF Compression= 1
HDF Chunk Size= 1
HDF Spatial Parts= 1
HDF Use Max Rows=0
HDF Fixed Rows= 1
Calibration Method= 0
Calibration Iterations= 20
Calibration Max Change=0.05
Calibration Tolerance=0.2
Calibration Maximum=1.5
Calibration Minimum=0.5
Calibration Optimization Method= 1
WQ AD Non Conservative
WQ ULTIMATE=-1
WQ Max Comp Step=1HOUR
WQ Output Interval=15MIN
WQ Output Selected Increments= 0
WQ Output face flow=0
WQ Output face velocity=0
WQ Output face area=0
WQ Output face dispersion=0
WQ Output cell volume=0
WQ Output cell surface area=0
WQ Output cell continuity=0
WQ Output cumulative cell continuity=0
WQ Output face conc=0
WQ Output face dconc_dx=0
WQ Output face courant=0
WQ Output face peclet=0
WQ Output face adv mass=0
WQ Output face disp mass=0
WQ Output cell mass=0
WQ Output cell source sink temp=0
WQ Output nsm pathways=0
WQ Output nsm derived pathways=0
WQ Output MaxMinRange=-1
WQ Daily Max Min Mean=-1
WQ Daily Range=0
WQ Daily Time=0
WQ Create Restart=0
WQ Fixed Restart=0
WQ System Summary=0
WQ Write To DSS=0
WQ Use Fixed Temperature=0
Sorting and Armoring Iterations= 10
XS Update Threshold= 0.02
Bed Roughness Predictor= 0
Hydraulics Update Threshold= 0.02
Energy Slope Method= 1
Volume Change Method= 1
Sediment Retention Method= 0
XS Weighting Method= 0
Number of US Weighted Cross Sections= 1
Number of DS Weighted Cross Sections= 1
Upstream XS Weight=0
Main XS Weight=1
Downstream XS Weight=0
Number of DS XS's Weighted with US Boundary= 1
Upstream Boundary Weight= 1
Weight of XSs Associated with US Boundary= 0
Number of US XS's Weighted with DS Boundary= 1
Downstream Boundary Weight= 0.5
Weight of XSs Associated with DS Boundary= 0.5
Percentile Method= 0
Sediment Output Level= 3
Mass or Volume Output= 0
Output Increment Type= 1
Profile and TS Output Increment= 1
XS Output Flag= 0
XS Output Increment= 10
Write Gradation File= 0
Read Gradation Hotstart= 0
Write HDF5 File= 1
Write Binary Output= 1
Write DSS Sediment File= 0
SV Curve= 0
Specific Gage Flag= 0

--- BLLKCK.f01 (steady flow) ---

Flow Title=Flow
Program Version=5.07
Number of Profiles= 6
Profile Names=01pct,10pct,04pct,02pct,0_2pct,01plus
River Rch & RM=BLLKCK,Main            ,12328
     582     308     409     492     812     860
River Rch & RM=BLLKCK,Main            ,11328
     645     342     454     547     899     954
River Rch & RM=BLLKCK,Main            ,9589
     715     381     505     607     995    1060
River Rch & RM=BLLKCK,Main            ,7581
     793     424     561     673    1100    1170
River Rch & RM=BLLKCK,Main            ,4333
    1180     641     841    1000    1630    1740
River Rch & RM=BLLKCK,Main            ,4083
    1220     663     869    1040    1680    1800
Boundary for River Rch & Prof#=BLLKCK,Main            , 1
Up Type= 0
Dn Type= 3
Dn Slope=0.01033
Boundary for River Rch & Prof#=BLLKCK,Main            , 2
Up Type= 0
Dn Type= 3
Dn Slope=0.01033
Boundary for River Rch & Prof#=BLLKCK,Main            , 3
Up Type= 0
Dn Type= 3
Dn Slope=0.01033
Boundary for River Rch & Prof#=BLLKCK,Main            , 4
Up Type= 0
Dn Type= 3
Dn Slope=0.01033
Boundary for River Rch & Prof#=BLLKCK,Main            , 5
Up Type= 0
Dn Type= 3
Dn Slope=0.01033
Boundary for River Rch & Prof#=BLLKCK,Main            , 6
Up Type= 0
Dn Type= 3
Dn Slope=0.01033
DSS Import GetInterval= 0
DSS Import GetPeak= 0
DSS Import FillOption= 0

--- BLLKCK.g01 (geometry) ---

Geom Title=Geometry
Program Version=5.07

River Reach=BLLKCK          ,Main
Reach XY= 30
      2057762.87      172803.274     2058118.425      173309.524
     2058109.901      174409.694     2058149.675      174560.219
     2058360.786      174812.302     2058390.821      175251.625
     2058519.945      175455.618      2058294.93      175861.651
      2058228.22      176462.085     2058144.925      176535.603
     2058165.199      176726.148      2058084.47      176831.356
     2058150.095      177095.939     2057977.699      177604.272
     2057713.636      177607.397     2057204.782      178096.981
      2057088.81      178314.978     2056910.338      178223.312
     2056416.366      178361.173     2056088.582      178712.038
     2056100.388       178932.09     2055959.416      179267.507
     2055813.481      179293.896     2054980.249      179911.951
      2054539.87      179981.396     2054387.193      180214.035
     2053644.138      180280.701     2053555.249      180341.118
     2053364.971      180781.396      2052877.64        180811.5

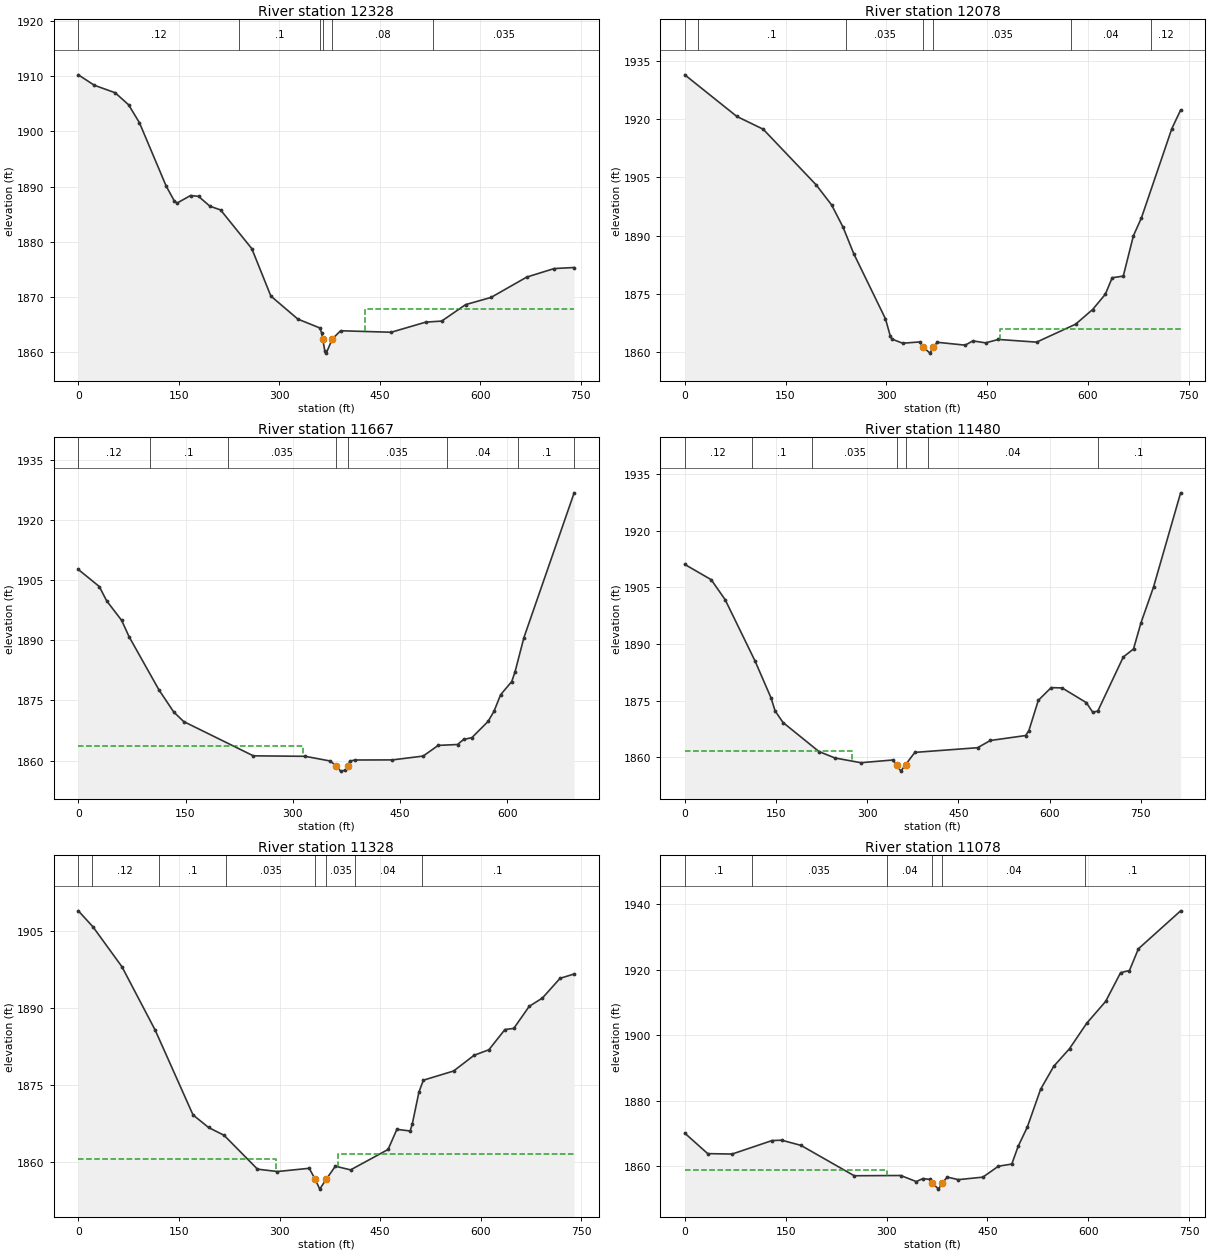
Type RM Length L Ch R = 1 ,12328   ,247.4,250,255.5
XS GIS Cut Line= 3
     2057468.313      173023.148     2057769.941      172810.345
     2057978.494      172503.782
#Sta/Elev= 30
       0 1910.22    23.9 1908.33    54.9 1906.98      75  1904.8    91.1 1901.57
   131.2 1890.05   143.3 1887.38   147.3    1887   167.4 1888.37   179.4 1888.22
   196.3 1886.44   212.3 1885.76   258.9 1878.75   287.3 1870.17   327.6    1866
   360.1 1864.41     363 1863.56   364.6 1862.46   367.7 1860.31     370 1859.84
   378.91862.397   391.4 1863.89   466.9 1863.62   518.4 1865.45   542.2 1865.64
   577.9 1868.62   615.8 1869.92   669.2 1873.61   710.1 1875.15   739.9 1875.34
#Mann= 6 ,-1 , 0
       0     .12       0     240      .1       0     360     .08       0
   364.6    .045       0   378.9     .08       0  529.14    .035       0
#XS Ineff= 2 , 0
                          428.48         1867.85
Permanent Ineff=
       F       F
Bank Sta=364.6,378.9
XS Rating Curve= 0 ,0
Exp/Cntr=0.3,0.1

Type RM Length L Ch R = 1 ,12078   ,403.2,410.9,413.6
XS GIS Cut Line= 3
     2057545.926      173167.613     2057874.156      173009.371
     2058197.353      172821.656
#Sta/Elev= 30
       0 1931.39    77.5 1920.68   116.7  1917.4   195.5 1903.09   218.6 1897.91
   235.7 1892.15   251.4 1885.42   298.7 1868.62     306 1864.12   308.5  1863.4
   324.3 1862.34   349.8 1862.67   354.61861.377     365 1859.79  370.22 1861.35
   375.7 1862.58   417.4 1861.84   428.8 1862.94   447.8 1862.43   466.8 1863.31
   523.7 1862.62   581.8 1867.24   607.1 1871.01   626.1 1874.96   636.2 1879.19
   652.7  1879.6   667.8 1889.98   679.8 1894.61     725 1917.55   738.1 1922.34
#Mann= 7 ,-1 , 0
       0     .12       0      20      .1       0     240    .035       0
   354.6    .045       0  370.22    .035       0  574.38     .04       0
  694.38     .12       0
#XS Ineff= 2 , 0
                          469.76         1866.11
Permanent Ineff=
       F       F
Bank Sta=354.6,370.22
XS Rating Curve= 0 ,0
Exp/Cntr=0.3,0.1

Type RM Length L Ch R = 1 ,11667   ,183.5,186.7,187.9
XS GIS Cut Line= 4
2057764.42160773173432.076599023 2058054.6517246173330.307597005
2058231.80517256173309.576874372 2058424.0355097173230.423206136
#Sta/Elev= 30
       0 1907.61    29.3 1903.37    39.7 1899.78    60.6 1894.94      71 1890.87
   112.8 1877.63   133.6 1872.09   147.5 1869.73   244.9  1861.2   317.4 1861.08
   351.9 1859.93     361 1858.75   366.9 1857.39   373.5 1857.61   376.8 1858.73
   380.1 1859.87   386.7 1860.16   439.6 1860.19   482.5 1861.14   503.6  1863.8
   530.6 1864.02     539 1865.27   550.7 1865.73   573.3 1869.76   581.6 1872.27
   590.9 1876.42   606.5 1879.71     611 1882.07   623.5 1890.64   693.8  1926.7
#Mann= 8 ,-1 , 0
       0     .12       0     100      .1       0     210    .035       0
     361    .045       0   376.8    .035       0  515.92     .04       0
  615.92      .1       0  693.81     .12       0
#XS Ineff= 2 , 0
           313.9 1863.65
Permanent Ineff=
       F       F
Bank Sta=361,376.8
XS Rating Curve= 0 ,0
Exp/Cntr(USF)=0,0
Exp/Cntr=0.3,0.1

Type RM Length L Ch R = 1 ,11480   ,150.4,152.4,151.5
XS GIS Cut Line= 3
     2057755.348      173487.099     2058224.098      173510.536
     2058440.011       173239.77
#Sta/Elev= 30
       0 1911.05    43.4 1907.01    66.3 1901.74   115.6 1885.47   141.9  1875.7
   148.5 1872.28   161.6  1869.2   220.7 1861.51     247 1859.81   289.7 1858.56
   342.3 1859.28   348.3 1857.99   355.4 1856.33   363.3 1858.07   378.4 1861.29
   481.6 1862.53   502.6 1864.44   560.5 1865.75   565.9 1867.01   581.5 1875.07
   602.6 1878.43   620.6 1878.36   660.5 1874.46     671 1871.93   679.3 1872.22
   721.3 1886.54   738.1 1888.67   750.3 1895.55     771 1905.05   815.6    1930
#Mann= 7 ,-1 , 0
       0     .12       0     110      .1       0     210    .035       0
   348.3    .045       0   363.3    .035       0     400     .04       0
  679.34      .1       0
#XS Ineff= 2 , 0
          275.54 1861.76
Permanent Ineff=
       F       F
Bank Sta=348.3,363.3
XS Rating Curve= 0 ,0
Exp/Cntr=0.3,0.1

Type RM Length L Ch R = 1 ,11328   ,249.8,250,247
XS GIS Cut Line= 3
     2057747.448      173599.016      2058105.93      173649.793
     2058482.367      173673.582
#Sta/Elev= 30
       0 1908.85    21.9 1905.72      65 1897.96   114.7 1885.57     171 1869.08
   194.2 1866.63   217.4  1865.1   267.1 1858.51   296.9 1858.05   344.2 1858.68
  353.231856.509   359.9 1854.62   369.6 1856.55   383.2 1859.09   405.9 1858.37
   461.8 1862.35   474.9 1866.27   494.7 1865.95     498 1867.39   507.8 1873.54
   514.4 1875.85   559.5 1877.64     590  1880.7   612.1 1881.78     636 1885.72
   649.2 1885.94   672.2 1890.24   691.9 1891.86   718.2  1895.7   739.2 1896.54
#Mann= 8 ,-1 , 0
       0      .1       0      20     .12       0     120      .1       0
     220    .035       0  353.23    .045       0   369.6    .035       0
  412.06     .04       0  512.06      .1       0
#XS Ineff= 2 , 0
          294.74 1860.54  387.39         1861.41
Permanent Ineff=
       F       F
Bank Sta=353.23,369.6
XS Rating Curve= 0 ,0
Exp/Cntr=0.3,0.1

Type RM Length L Ch R = 1 ,11078   ,184,182.9,183.5
XS GIS Cut Line= 3
     2057764.722      173855.056      2058138.02      173894.826
     2058497.526       173852.53
#Sta/Elev= 30
       0 1870.05    34.1 1863.79    70.4 1863.67   129.8 1867.79     144  1867.9
   172.7 1866.32   251.9 1857.04   321.2 1857.11   344.3 1855.25   354.2 1856.19
   364.1 1855.91   367.9 1854.91   377.3 1852.95   382.91854.896   390.5 1856.62
   406.8 1855.85   443.3 1856.61   466.4 1859.95   486.3 1860.61   495.8 1866.04
   509.4 1871.91   529.2 1883.47   548.7 1890.47   572.2 1895.87   597.7 1903.61
   625.9 1910.29   648.1 1919.06   661.3 1919.73   674.6 1926.36   737.4 1937.96
#Mann= 6 ,-1 , 0
       0      .1       0     100    .035       0     300     .04       0
   367.9    .045       0   382.9     .04       0  595.41      .1       0
#XS Ineff= 2 , 0
          300.17 1858.94
Permanent Ineff=
       F       F
Bank Sta=367.9,382.9
XS Rating Curve= 0 ,0
Exp/Cntr=0.3,0.1

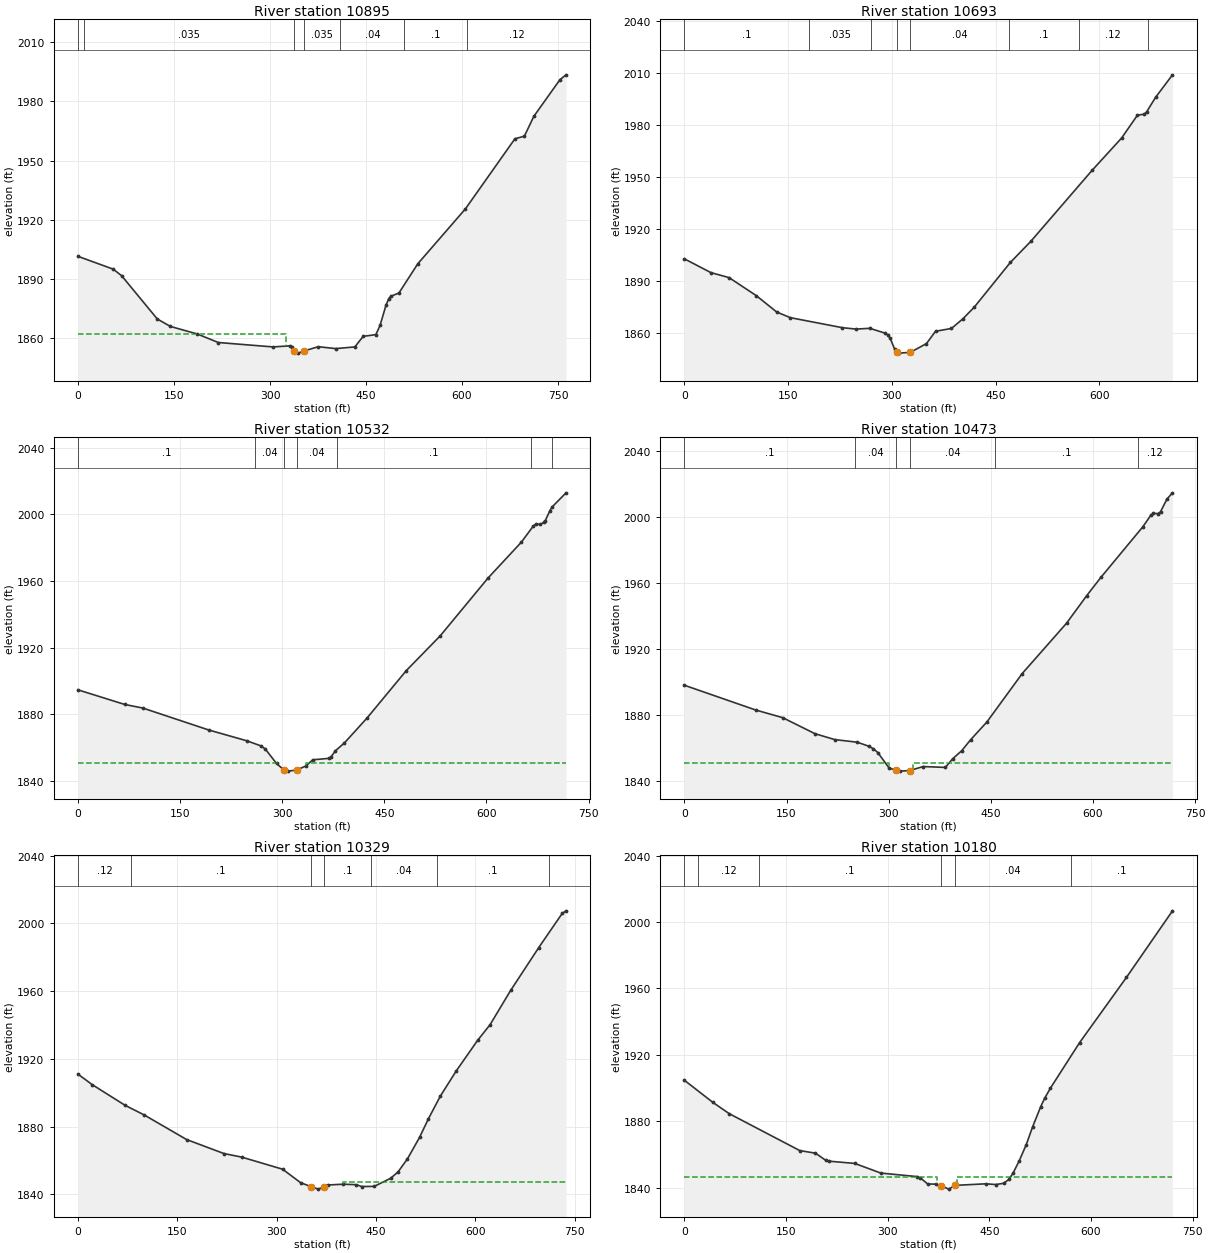
Type RM Length L Ch R = 1 ,10895   ,201.2,202.1,202
XS GIS Cut Line= 3
     2057750.139       174075.64     2058307.431      174062.619
     2058489.723      174156.369
#Sta/Elev= 30
       0 1901.43    55.1 1894.91    68.2  1891.6     124 1869.62   144.5 1865.85
   186.4 1862.03   219.2 1857.71   304.5 1855.47   330.7    1856     334 1855.58
     3381853.351   343.9 1852.32     353 1853.41   375.4 1855.57   402.9 1854.62
   432.5 1855.47   445.6 1860.84   465.3  1861.7   471.9 1866.36   481.2 1876.64
   485.6 1879.98   488.3 1881.11   501.4 1882.83   530.9 1897.66   605.2 1925.48
   682.6 1961.07   697.3 1962.35   712.1 1972.43   752.7 1990.95   762.4 1993.49
#Mann= 7 ,-1 , 0
       0      .1       0      10    .035       0     338    .045       0
     353    .035       0     410     .04       0     510      .1       0
  607.44     .12       0
#XS Ineff= 2 , 0
           325.5 1861.96
Permanent Ineff=
       F       F
Bank Sta=338,353
XS Rating Curve= 0 ,0
Exp/Cntr=0.3,0.1

Type RM Length L Ch R = 1 ,10693   ,163.2,160.8,158.2
XS GIS Cut Line= 2
     2057786.598      174260.536     2058492.327      174268.349
#Sta/Elev= 30
       0 1902.95    38.3 1895.01    64.5 1892.15   103.9 1881.76   133.4 1872.33
   153.1 1869.06   228.6 1863.27   248.3 1862.47     268 1862.92   289.7  1860.2
   294.2 1859.07   297.5 1857.22   304.1 1850.82   306.91849.306   310.6 1848.62
   326.81849.075     350 1854.11   363.1  1861.2   386.1 1862.83   402.5 1868.31
   419.1 1875.09   471.4  1900.9   500.9 1913.02   589.5 1953.93   632.2 1972.56
   655.1 1985.72     665 1986.32   668.3 1987.57   681.4 1996.04   705.8 2008.98
#Mann= 8 ,-1 , 0
       0      .1       0     180    .035       0     270     .04       0
   306.9    .045       0   326.8     .04       0     470      .1       0
     570     .12       0     670      .1       0
Bank Sta=306.9,326.8
XS Rating Curve= 0 ,0
Exp/Cntr=0.5,0.3

Type RM Length L Ch R = 1 ,10532   ,59.4,59,59.5
XS GIS Cut Line= 3
     2057802.825      174474.316     2058242.785      174402.398
     2058496.571      174307.471
#Sta/Elev= 30
       0 1894.76    68.9 1885.97    95.5 1883.81   191.9  1870.7   248.4 1864.15
   268.4 1861.19     275 1859.34   291.6 1850.61  302.741846.605   308.3    1846
   321.21846.643   334.9 1849.13   344.8  1852.8   368.1 1853.64   371.4  1854.4
   378.1  1858.2   391.4 1862.94   424.4 1877.77   482.1 1906.25   532.1 1927.18
   602.1 1961.75   651.2 1983.35   668.7 1992.97   672.2 1994.09   679.2 1994.05
   684.2 1995.14   686.2 1996.14   693.2 2002.29   696.7 2004.61   716.8 2012.93
#Mann= 7 ,-1 , 0
       0      .1       0     260     .04       0  302.74    .045       0
   321.2     .04       0     380      .1       0   665.8     .12       0
   695.8      .1       0
#XS Ineff= 2 , 0
          293.01 1851.02  334.27         1850.88
Permanent Ineff=
       F       F
Bank Sta=302.74,321.2
XS Rating Curve= 0 ,0
Exp/Cntr=0.5,0.3

Type RM Length L Ch R = 1 ,10473   ,150.3,144.2,136.4
XS GIS Cut Line= 3
     2057810.305      174532.872     2058250.265      174460.954
     2058504.051      174366.027
#Sta/Elev= 30
       0 1898.17   104.5  1883.2   144.4 1878.53   191.7 1868.84   220.9 1865.25
   254.1 1863.66   270.8 1861.22   277.4 1859.77   284.1 1857.37   300.7 1847.99
   311.41846.635   317.3 1846.16   331.11846.524   350.5 1848.93   383.2 1848.41
   393.8 1853.58   407.1 1858.47   420.4 1865.19   444.3 1875.97   496.1 1905.26
   561.2 1935.74   590.6 1952.32   611.5 1963.43   672.9 1993.96   685.2 2001.24
   688.7 2002.21   695.8 2002.16   699.2 2003.25   708.6  2010.9   716.8 2014.71
#Mann= 6 ,-1 , 0
       0      .1       0     250     .04       0   311.4    .045       0
   331.1     .04       0   455.8      .1       0   665.8     .12       0
#XS Ineff= 2 , 0
          300.86 1850.95  335.37          1850.8
Permanent Ineff=
       F       F
Bank Sta=311.4,331.1
XS Rating Curve= 0 ,0
Exp/Cntr=0.5,0.3

Type RM Length L Ch R = 1 ,10329   ,148.3,149.4,150.6
XS GIS Cut Line= 3
     2057899.811      174829.401     2058186.549      174608.373
     2058496.663      174397.327
#Sta/Elev= 30
       0 1910.96    21.4 1904.78    71.1 1892.55   100.1 1886.83   164.2  1872.3
   220.3 1864.07   247.4 1861.93   309.2 1854.78   336.2 1846.86   352.21844.472
   363.1 1843.03   371.81844.399     377 1845.47   400.8 1845.93   420.6 1845.65
   428.6 1844.58   447.5 1844.65   472.2 1849.42   483.5 1853.19   497.7 1860.93
   515.9 1873.55   529.2 1884.45   547.2 1897.86   571.4 1912.86   603.9 1931.03
   622.5 1940.16   653.5 1960.35     696  1985.7   731.4 2005.84   737.2 2007.39
#Mann= 7 ,-1 , 0
       0     .12       0      80      .1       0   352.2    .045       0
   371.8      .1       0  442.04     .04       0  542.04      .1       0
  712.04     .12       0
#XS Ineff= 2 , 0
                          400.66         1847.52
Permanent Ineff=
       F       F
Bank Sta=352.2,371.8
XS Rating Curve= 0 ,0
Exp/Cntr=0.5,0.3

Type RM Length L Ch R = 1 ,10180   ,37.6,37.9,37.2
XS GIS Cut Line= 2
     2057965.417      174912.793     2058578.264      174534.321
#Sta/Elev= 30
       0 1904.62      42 1891.31    66.2  1884.5   170.3 1862.27   193.4 1860.72
   208.9 1856.32   212.7 1855.92   251.3 1854.55   289.9 1848.72   343.8  1846.6
   347.7    1846     359 1842.18     371 1842.06   379.21841.077     390 1839.06
   399.4 1841.33   444.9 1842.26   459.5 1841.83   471.1 1842.57   478.8 1844.89
   485.4    1849   494.2  1856.2   504.5 1865.87     514 1876.73   525.9 1888.79
   531.5 1893.68   540.2 1899.92   583.1 1927.25   652.3 1966.56   720.3 2006.69
#Mann= 6 ,-1 , 0
       0      .1       0      20     .12       0     110      .1       0
   379.2    .045       0   399.4     .04       0     570      .1       0
#XS Ineff= 2 , 0
          372.67 1846.33  402.15         1846.48
Permanent Ineff=
       F       F
Bank Sta=379.2,399.4
XS Rating Curve= 0 ,0
Exp/Cntr=0.5,0.3

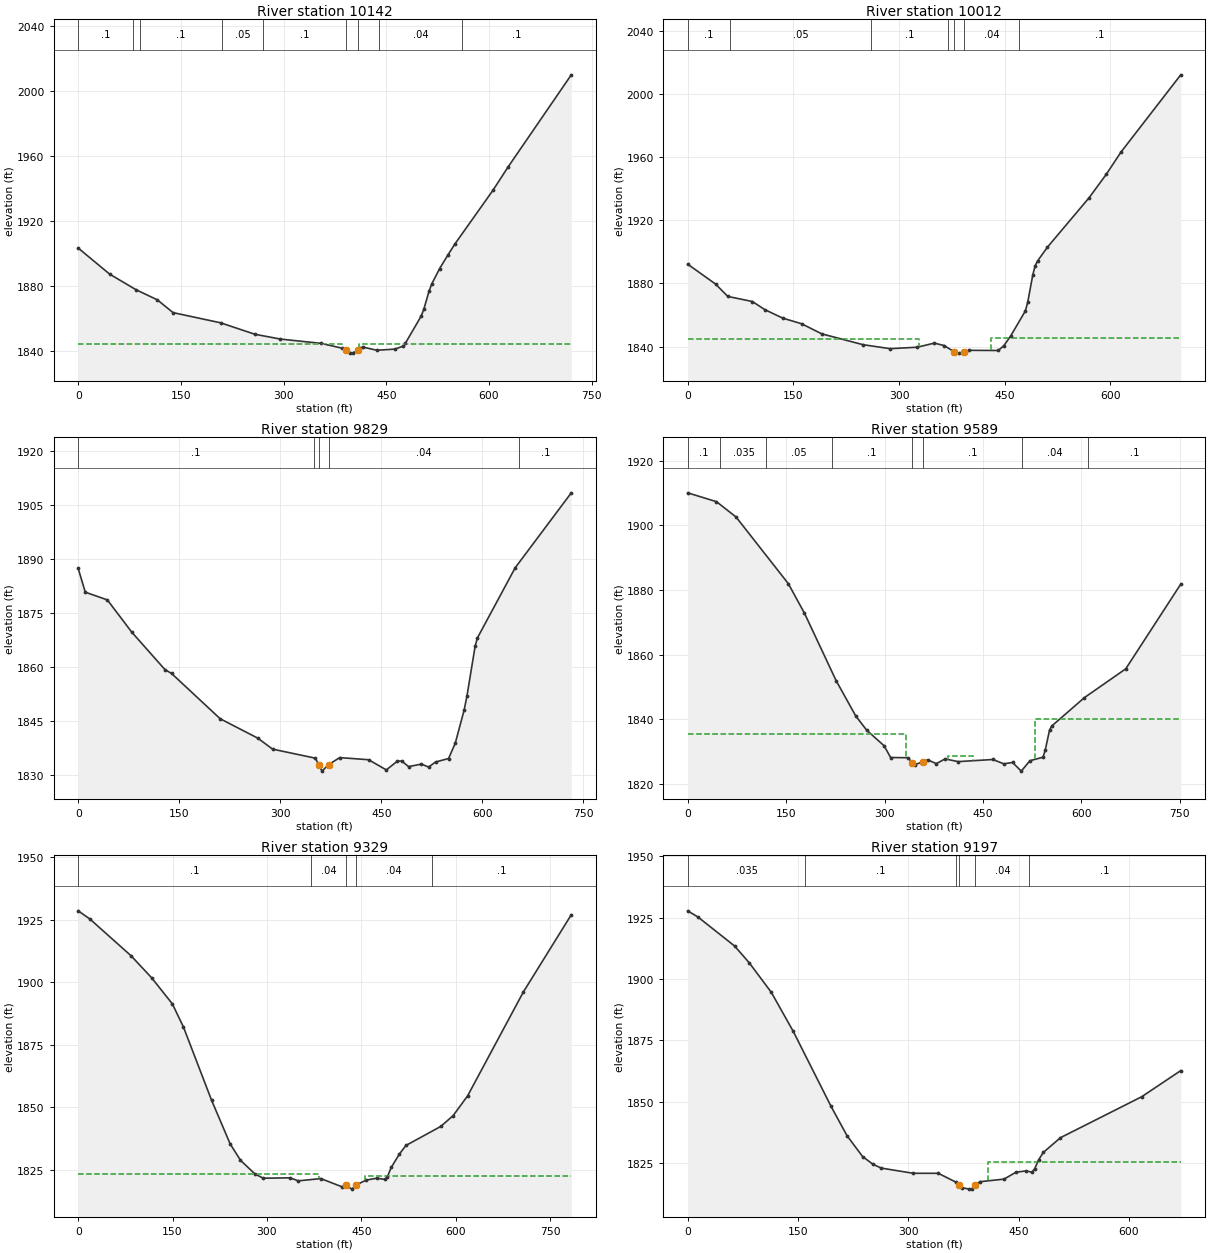
Type RM Length L Ch R = 1 ,10142   ,126.9,130.2,133
XS GIS Cut Line= 2
     2057979.306      174947.515     2058592.153      174569.043
#Sta/Elev= 30
       0 1903.17      46 1887.09    84.6 1877.45   115.4  1871.3   138.6 1863.37
     208 1857.09   258.1 1850.03   295.5 1847.06   354.5 1844.43   385.4 1841.47
  390.571840.209   396.9 1838.52   400.8  1838.4   409.31840.146   412.3 1841.54
   416.2 1842.12   436.2 1840.16   462.5 1840.87     474 1842.61   477.9 1844.47
     501 1861.22   504.9 1865.45   512.6 1876.72   516.5  1881.1     528 1890.55
   539.6 1898.58   550.6 1905.89   605.9  1938.8   628.3 1953.37   720.3 2009.95
#Mann= 9 ,-1 , 0
       0      .1       0      80     .12       0      90      .1       0
     210     .05       0     270      .1       0  390.57    .045       0
   409.3      .1       0     440     .04       0     560      .1       0
#XS Ineff= 2 , 0
          385.69 1843.93  410.67         1843.97
Permanent Ineff=
       F       F
Bank Sta=390.57,409.3
XS Rating Curve= 0 ,0
Exp/Cntr=0.5,0.3

Type RM Length L Ch R = 1 ,10012   ,178.3,182.6,187.8
XS GIS Cut Line= 3
2058007.53644589174986.8807965182058474.23483595 174817.32363398
2058666.22185015174750.049735092
#Sta/Elev= 30
       01892.255  39.5481879.652  57.0011871.792  91.9081868.568 109.3611863.472
 134.8141858.067 161.7211854.476 190.3961848.075 248.9871841.215 287.3841838.693
 326.0981839.622 350.2161842.229 364.1781840.644 378.1411836.792 385.1221835.866
 392.1041836.607 399.0851837.644 440.9731837.534 448.9981840.676 458.4261846.664
  479.371862.588 482.8611868.383 489.9651885.516 493.3331891.274 496.8221894.351
 510.7281903.029 569.7341934.257 594.1621949.119  615.021963.211 699.978 2012.22
#Mann= 7 ,-1 , 0
       0      .1       0      60     .05       0     260      .1       0
     370     .04       0 378.141    .045       0 392.104     .04       0
     470      .1       0
#XS Ineff= 2 , 0
          328.94 1844.71  430.23         1845.76
Permanent Ineff=
       F       F
Bank Sta=378.141,392.104
XS Rating Curve= 0 ,0
Exp/Cntr(USF)=0,0
Exp/Cntr=0.3,0.1

Type RM Length L Ch R = 1 ,9829    ,236.8,240.1,235.7
XS GIS Cut Line= 3
     2058001.452      175054.619     2058366.191      175036.569
     2058731.292      175000.076
#Sta/Elev= 30
       0 1887.31    10.5 1880.74    43.3 1878.59    79.4 1869.68   128.7 1859.29
   138.6  1858.2   210.8 1845.64   266.7 1840.26   288.6 1837.22   352.1 1834.71
   357.7 1832.69   361.9 1831.12   371.9 1832.94   388.3 1834.87   431.2 1834.28
   457.5 1831.45     474 1833.92   480.6  1833.9   490.5 1832.37   509.6 1833.07
   520.2 1832.26   530.6 1833.65   549.9 1834.62   559.8 1838.85   572.9 1847.96
   577.1 1851.84   589.4 1865.83   592.7 1868.05   648.8  1887.5   732.1 1908.28
#Mann= 5 ,-1 , 0
       0      .1       0     350     .04       0   357.7    .045       0
   371.9     .04       0  655.19      .1       0
Bank Sta=357.7,371.9
XS Rating Curve= 0 ,0
Exp/Cntr=0.3,0.1

Type RM Length L Ch R = 1 ,9589    ,259.6,259.9,261.5
XS GIS Cut Line= 2
   2058043.96128175306.4573599752058787.05333002175195.394250039
#Sta/Elev= 30
       01910.029  43.8791907.298  73.7341902.559 153.3491881.957 177.9651872.827
 226.3291851.923 256.1841841.023 272.7711836.655 299.3091831.827 309.2611828.198
 335.7991828.125 342.4331826.537 345.7511825.959  359.021826.897 365.6541827.496
 378.9231826.294 392.1931827.772 412.0961826.929 465.1731827.583 481.7591826.238
 495.0281826.674 508.2971823.988 521.5661827.216  541.471828.291 544.7871830.418
 551.4221836.692 554.7391837.935 604.4981846.706 667.5261855.613 751.3461881.804
#Mann= 8 ,-1 , 0
       0      .1       0      50    .035       0     120     .05       0
     220      .1       0 342.433    .045       0  359.02      .1       0
     510     .04       0     610      .1       0
#XS Ineff= 3 ,-1
       0   332.2 1835.62   396.8  434.26 1828.81  528.81 751.346 1840.07
Permanent Ineff=
       F       F       F
Bank Sta=342.433,359.02
XS Rating Curve= 0 ,0
Exp/Cntr=0.3,0.1

Type RM Length L Ch R = 1 ,9329    ,127.9,132.4,138
XS GIS Cut Line= 3
      2058088.58        175478.3     2058520.368       175468.33
      2058872.19      175456.604
#Sta/Elev= 30
       0 1928.65    18.5 1925.39    84.1 1910.65   116.9  1901.8   149.7 1891.39
   167.3 1882.16   212.1 1852.78   241.6 1835.35     258 1828.78     281 1823.32
   294.1 1821.61   336.8 1821.77   349.9 1820.55   385.7 1821.46   418.8 1818.23
   425.4  1818.8   435.2 1817.24   441.71818.896   458.2 1820.88   474.6 1821.61
   487.8 1821.12   491.1 1821.93   497.6 1825.91   510.7 1831.31     521 1834.72
   576.4 1842.34   596.1 1846.67   619.1 1854.59   707.6 1896.13   783.9 1927.09
#Mann= 5 ,-1 , 0
       0      .1       0     370     .04       0   425.4    .045       0
   441.7     .04       0   561.9      .1       0
#XS Ineff= 2 , 0
          382.22 1823.23  456.59         1822.63
Permanent Ineff=
       F       F
Bank Sta=425.4,441.7
XS Rating Curve= 0 ,0
Exp/Cntr=0.3,0.1

Type RM Length L Ch R = 1 ,9197    ,185,191,193
XS GIS Cut Line= 4
2058099.88239216175514.571918092 2058420.2662874 175567.34103025
2058550.30445665175618.2255312592058723.68868231175729.417589019
#Sta/Elev= 30
       0 1927.82    13.9 1925.32    63.8 1913.49    83.7 1906.65   113.7 1894.61
   143.6 1878.66     195 1848.08   216.7 1836.15   237.8 1827.68   252.1 1824.49
   263.3 1822.97   306.5 1820.86   340.7 1820.85   364.1 1817.33   368.8 1815.93
   372.4 1815.02   382.9  1814.4   386.5 1814.58   391.2 1816.01     397 1817.41
     430 1818.48   446.3 1821.28   460.4 1821.85   467.8 1821.27   471.7 1822.68
   477.2  1826.4   483.4 1829.34   506.8 1835.37   617.3 1852.07   670.3 1862.71
#Mann= 6 ,-1 , 0
       0    .035       0     160      .1       0   364.7     .04       0
   368.8    .045       0   391.2     .04       0  464.34      .1       0
#XS Ineff= 2 , 0
                          408.17         1825.53
Permanent Ineff=
       F       F
Bank Sta=368.8,391.2
XS Rating Curve= 0 ,0
Exp/Cntr(USF)=0,0
Exp/Cntr=0.3,0.1

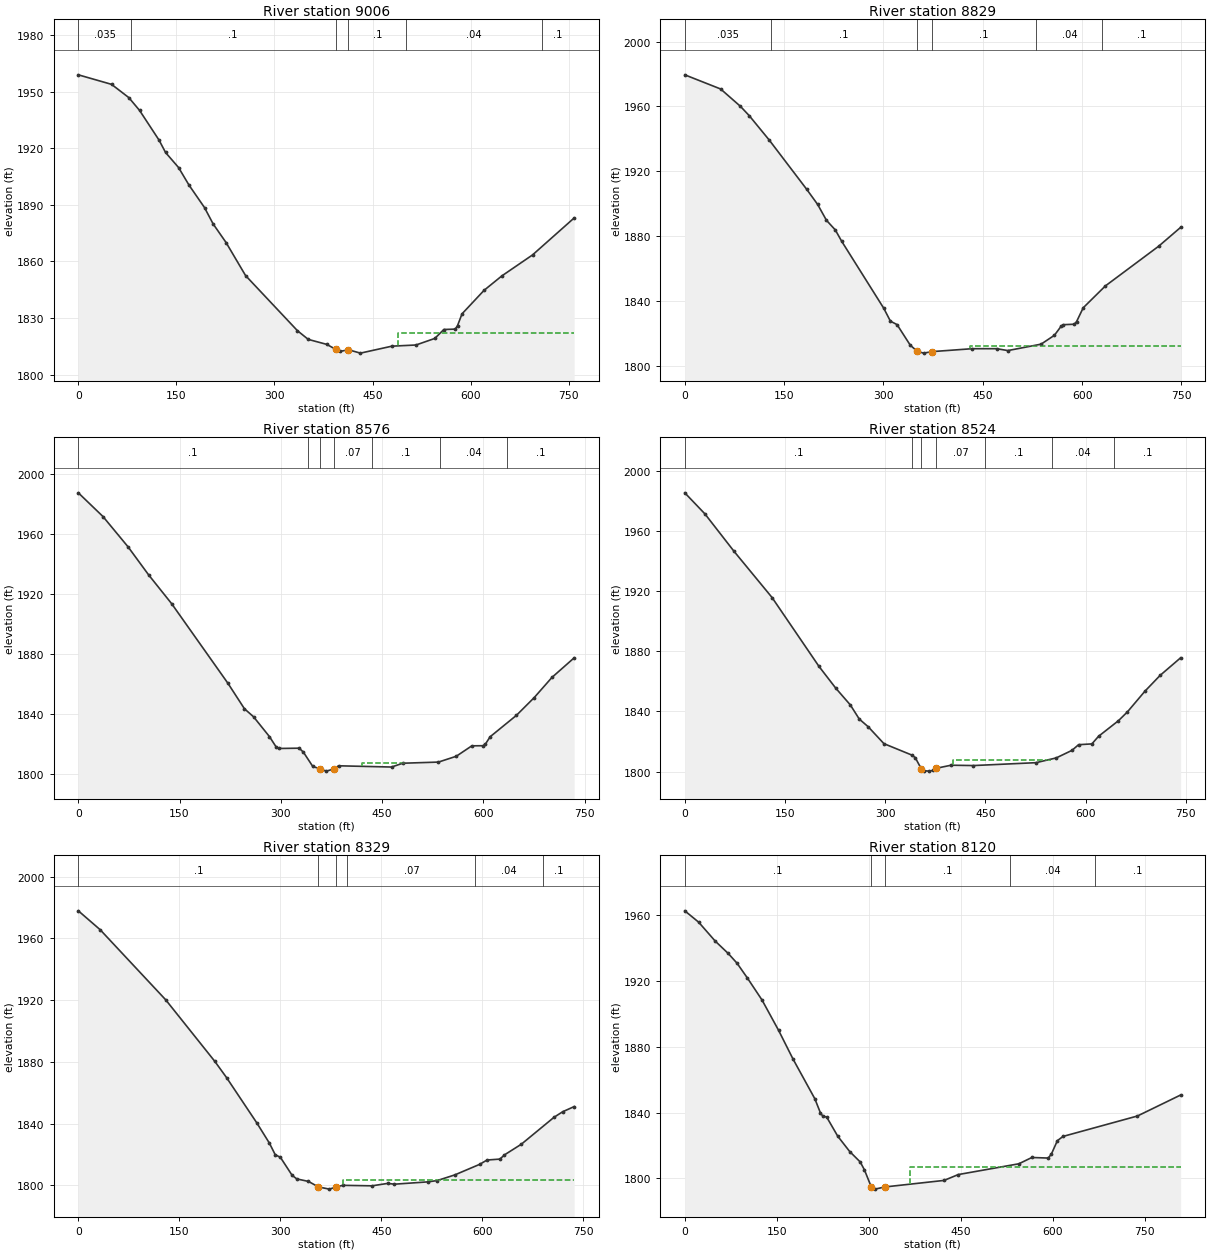
Type RM Length L Ch R = 1 ,9006    ,182.3,176.6,168.7
XS GIS Cut Line= 4
     2057984.514      175674.599     2058333.473      175718.869
     2058479.306      175820.432     2058695.452      175895.953
#Sta/Elev= 30
       0 1958.99    50.8 1953.94    77.2 1946.92    93.7  1940.1   123.5 1924.34
   133.4 1917.81   153.3 1909.82   169.3 1900.49     193 1888.58   206.2  1879.9
     226 1870.03   255.8 1852.52   335.2 1823.26   351.7 1818.66   379.8 1816.04
   393.8 1813.38   399.7 1812.26   413.21813.149   431.5 1811.38   479.6 1815.07
   516.4 1815.69   545.2 1819.17   559.1 1823.91   576.5 1824.12     580 1825.96
   586.9 1832.22   620.7 1844.72   647.8 1852.34   694.7 1863.46   758.4 1883.07
#Mann= 6 ,-1 , 0
       0    .035       0      80      .1       0   393.8    .045       0
   413.2      .1       0  501.76     .04       0  709.47      .1       0
#XS Ineff= 2 , 0
                          488.25         1822.27
Permanent Ineff=
       F       F
Bank Sta=393.8,413.2
XS Rating Curve= 0 ,0
Exp/Cntr=0.3,0.1

Type RM Length L Ch R = 1 ,8829    ,251.3,253,251.5
XS GIS Cut Line= 3
     2057935.664      175835.357     2058290.892      175897.466
     2058671.064      175975.457
#Sta/Elev= 30
       0 1979.48    54.1 1970.75    83.9 1960.09    97.4 1954.25   127.4  1939.3
     184 1908.92   200.6 1899.54   213.9 1889.76   227.3  1883.8     237 1876.75
   300.5 1835.46   310.5 1827.54   320.5 1825.43   340.5 1812.71   350.81809.056
   360.5 1807.84   373.71808.779   433.9 1810.57     471 1810.58   487.8 1809.41
     538 1813.37   558.1 1818.84   568.1 1824.34   571.5 1825.38   588.2 1825.67
   591.6 1827.28   601.6  1835.8   635.1 1849.29   715.5 1873.76   748.7 1885.39
#Mann= 6 ,-1 , 0
       0    .035       0     130      .1       0   350.8    .045       0
   373.7      .1       0  530.62     .04       0  630.62      .1       0
#XS Ineff= 2 , 0
                          431.26         1812.21
Permanent Ineff=
       F       F
Bank Sta=350.8,373.7
XS Rating Curve= 0 ,0
Exp/Cntr=0.5,0.3

Type RM Length L Ch R = 1 ,8576    ,52.3,52.2,51.9
XS GIS Cut Line= 4
2057927.22917706176052.2784480932058259.94228999176134.590285925
2058330.99040264176150.186213094 2058648.1075884176185.710269422
#Sta/Elev= 30
       0 1987.69    36.5 1971.86    73.7 1951.59   104.1  1932.9   138.3  1913.6
   221.8 1860.34   246.1 1843.43   259.6 1838.07   283.2  1824.8   293.4 1817.68
   296.8 1816.89   327.2 1817.09   333.4 1814.46   347.4 1804.86     358 1803.31
   367.6 1801.76   378.3 1803.18   385.6 1805.32   464.1  1804.5   480.7 1807.04
   533.5  1807.8   559.9 1811.68     583 1818.66   599.5 1818.74   602.8  1819.6
   610.1 1824.72     649    1839   675.4 1850.88   701.8 1864.41   734.6 1877.45
#Mann= 7 ,-1 , 0
       0      .1       0     340     .07       0     358    .045       0
   378.3     .07       0  435.48      .1       0  535.48     .04       0
  635.48      .1       0
#XS Ineff= 3 ,-1
  339.35  352.45 1803.35  382.11  394.18 1803.37  420.73  487.28 1807.04
Permanent Ineff=
       F       F       F
Bank Sta=358,378.3
XS Rating Curve= 0 ,0
Exp/Cntr(USF)=0,0
Exp/Cntr=0.5,0.3

Type RM Length L Ch R = 1 ,8524    ,190.7,194.8,193.1
XS GIS Cut Line= 3
     2057916.806      176117.307     2058497.535      176237.099
     2058645.973      176221.474
#Sta/Elev= 30
       0 1985.22    30.1 1971.24    73.6 1946.42   130.6 1915.69   200.9 1869.91
     226 1855.47   247.8 1844.34   261.2 1834.95   274.6 1829.82   298.1 1818.62
     340 1811.02     345 1809.32   353.8 1802.09   358.4 1800.68   364.9 1800.38
   371.8 1800.85   376.71802.301   398.6 1804.31   432.1 1804.08   525.8 1805.99
     556 1809.16   579.5 1814.16   589.5 1817.94   609.4 1818.47   619.3  1823.5
     649 1833.82   662.6 1839.74   688.7 1853.43   711.6 1864.01   742.2 1875.65
#Mann= 7 ,-1 , 0
       0      .1       0     340     .07       0   353.8    .045       0
   376.7     .07       0     450      .1       0     550     .04       0
  642.96      .1       0
#XS Ineff= 3 ,-1
  333.65  348.15 1802.19  380.33  393.47 1802.39  401.63  550.73 1807.56
Permanent Ineff=
       F       F       F
Bank Sta=353.8,376.7
XS Rating Curve= 0 ,0
Exp/Cntr=0.5,0.3

Type RM Length L Ch R = 1 ,8329    ,207.8,208.8,207.9
XS GIS Cut Line= 3
     2057886.178      176255.696     2058235.181      176377.765
     2058596.068      176442.569
#Sta/Elev= 30
       0 1977.81    32.4 1965.59   129.7 1920.21   202.7 1880.32   220.1 1869.83
   265.3 1840.31   283.8 1827.34   292.4 1819.88   300.1 1818.17   317.4  1806.6
   324.4 1804.18   341.7 1802.58   356.61798.987   372.9 1797.57   382.81798.949
   392.9 1800.03   436.2 1799.71   459.5 1801.28   469.5 1800.77   519.4 1802.28
   532.9 1803.11     559 1806.76   596.2 1813.65     607 1816.42   626.2 1817.02
   632.9 1819.75   657.9 1826.64   706.6 1844.13   719.5 1847.72   736.4 1851.02
#Mann= 6 ,-1 , 0
       0      .1       0   356.6    .045       0   382.8      .1       0
  399.73     .07       0  589.73     .04       0  689.73      .1       0
#XS Ineff= 2 , 0
                          392.99          1803.5
Permanent Ineff=
       F       F
Bank Sta=356.6,382.8
XS Rating Curve= 0 ,0
Exp/Cntr=0.3,0.1

Type RM Length L Ch R = 1 ,8120    ,219.4,222.7,218.3
XS GIS Cut Line= 3
     2057841.285      176458.453     2058380.348       176606.89
      2058544.41       176794.39
#Sta/Elev= 30
       0 1962.63    22.5 1955.77    49.6 1944.23    70.5 1936.84    85.1 1930.84
   102.1 1921.78   125.9 1908.44     153 1889.95   176.4 1872.59     212 1848.44
   221.2 1839.78   224.6 1838.09   231.4 1837.26   249.3 1825.72   268.8  1816.4
   285.9 1810.07   292.7 1805.37   304.11794.799   309.7 1793.54     3271794.895
   422.7 1798.84   445.8 1802.39   544.5 1808.93   565.8 1812.76   592.5 1812.42
   597.5 1814.76   607.4 1822.99   616.6 1825.57   737.9 1837.97   808.3 1850.73
#Mann= 5 ,-1 , 0
       0      .1       0   304.1    .045       0     327      .1       0
     530     .04       0  669.13      .1       0
#XS Ineff= 2 , 0
                          366.76         1807.06
Permanent Ineff=
       F       F
Bank Sta=304.1,327
XS Rating Curve= 0 ,0
Exp/Cntr=0.3,0.1

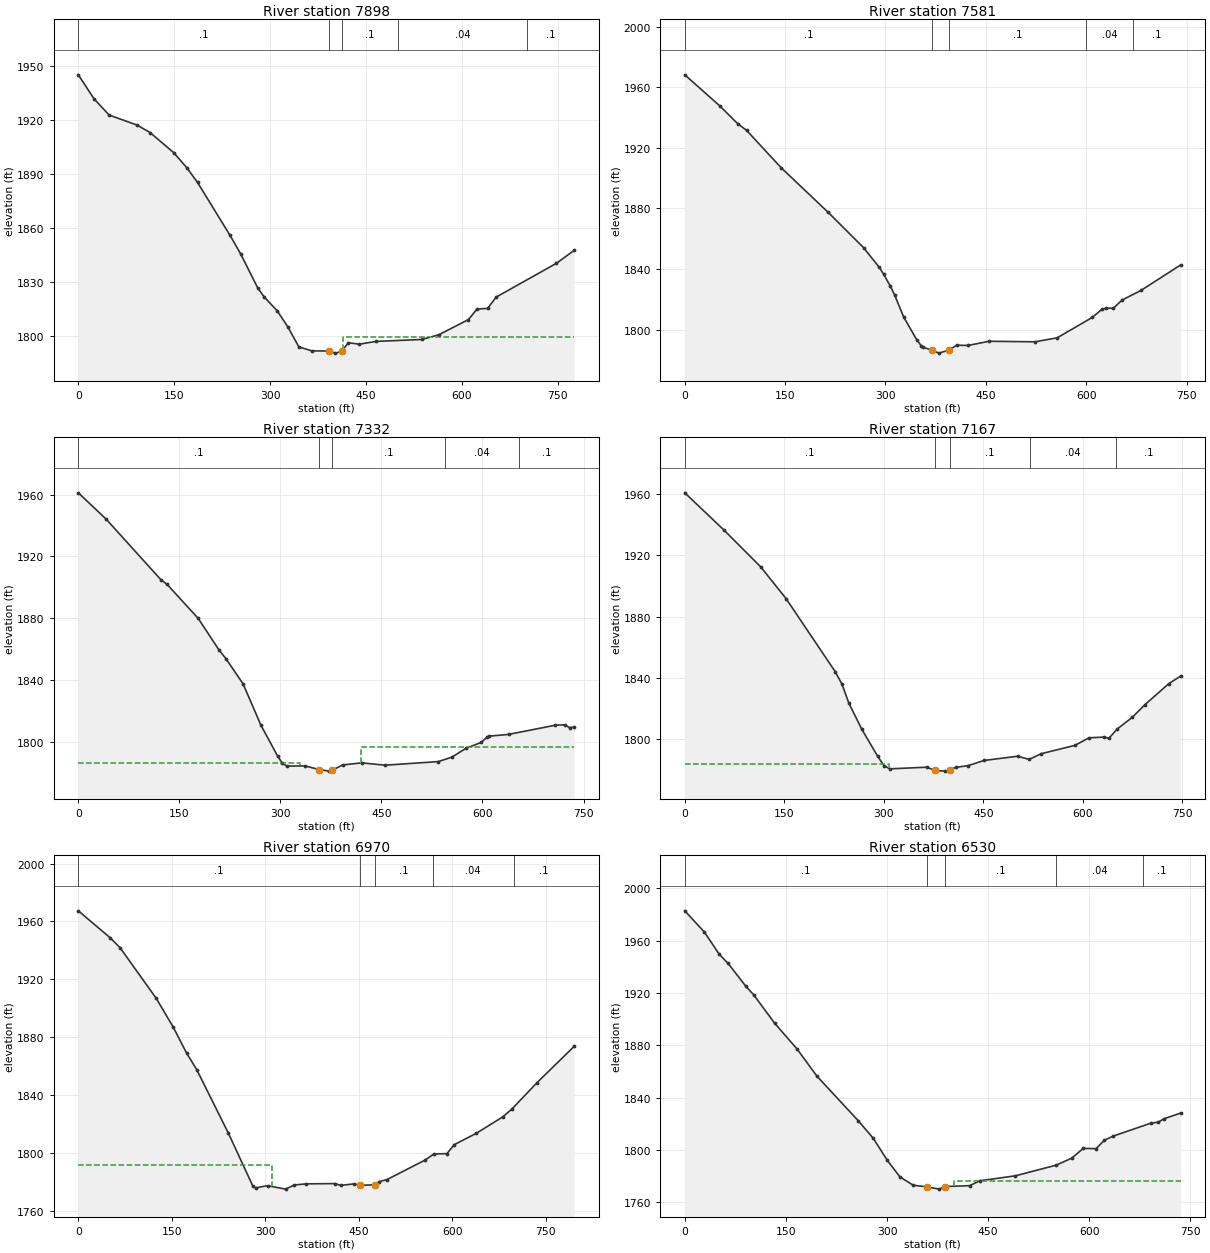
Type RM Length L Ch R = 1 ,7898    ,320,316.2,297.8
XS GIS Cut Line= 3
     2057768.151        176664.12058295.33036008176788.792549992
2058525.98590002176827.332639973
#Sta/Elev= 30
       01945.019  24.662 1931.63  48.1921922.661  92.0191917.053 112.2481912.925
 149.3331901.696 169.5611893.423 186.4171885.187 236.9881855.965 253.8451845.495
 280.8161826.426  290.931821.407 311.1581813.805 328.0151804.714 344.8711793.772
 365.099 1791.56  392.07 1791.43 402.1841790.287 411.8211791.273 422.4131796.086
 439.2691795.258  466.241796.825 537.0391797.871 563.7121800.463  610.281808.953
 623.5861814.791 640.2171815.142 653.5221821.428 747.9421840.251 775.5791847.422
#Mann= 5 ,-1 , 0
       0      .1       0  392.07    .045       0 411.821      .1       0
     500     .04       0  701.73      .1       0
#XS Ineff= 2 , 0
                          413.75         1799.41
Permanent Ineff=
       F       F
Bank Sta=392.07,411.821
XS Rating Curve= 0 ,0
Exp/Cntr=0.3,0.1

Type RM Length L Ch R = 1 ,7581    ,242.2,249.6,260.1
XS GIS Cut Line= 3
     2057762.783      177071.622     2058140.252      177027.467
     2058494.729      176958.274
#Sta/Elev= 30
       0 1968.19    52.6 1947.57      79 1935.96    92.3 1931.57   143.9 1906.95
   214.5 1877.38   267.2 1854.15   290.5 1841.29   297.1 1836.75     307 1828.97
   313.6 1822.97   327.2 1808.39   346.6 1793.44   353.2 1789.57   356.5  1788.4
   370.21786.368   379.6 1784.55  394.831786.492   406.4 1789.78   423.1  1789.6
   455.2 1792.39   523.4 1792.01   556.8 1794.68   609.1  1808.1   623.7  1813.5
   630.3 1814.25   640.4 1814.13   653.7 1819.57   681.8 1825.89   741.2 1842.72
#Mann= 5 ,-1 , 0
       0      .1       0   370.2    .045       0  394.83      .1       0
  600.04     .04       0  670.04      .1       0
Bank Sta=370.2,394.83
XS Rating Curve= 0 ,0
Exp/Cntr=0.3,0.1

Type RM Length L Ch R = 1 ,7332    ,159.9,164.7,166.6
XS GIS Cut Line= 3
     2057753.449      177143.492     2058105.278      177270.115
     2058424.711      177440.856
#Sta/Elev= 30
       0  1961.1    41.1 1944.19   122.4 1905.05   131.8 1901.93     178 1879.96
   208.4 1859.86   219.3 1853.86   244.6 1837.67   271.2 1810.85   295.9    1791
   302.6 1786.52   309.5 1784.57   336.9 1784.63   357.51782.334   372.3  1781.3
   377.21781.968   392.3 1785.28   420.6 1786.65   455.3 1785.14   534.3 1787.45
   554.5 1790.33     576 1796.17   598.3 1799.87   606.6 1803.29   610.3 1803.91
   638.7 1805.03   708.3 1810.98   721.9 1811.18   729.3 1809.42   736.1 1809.71
#Mann= 5 ,-1 , 0
       0      .1       0   357.5    .045       0   377.2      .1       0
  543.92     .04       0  653.92      .1       0
#XS Ineff= 2 , 0
          329.41 1786.72  419.48         1797.06
Permanent Ineff=
       F       F
Bank Sta=357.5,377.2
XS Rating Curve= 0 ,0
Exp/Cntr=0.3,0.1

Type RM Length L Ch R = 1 ,7167    ,188.8,196.9,201.8
XS GIS Cut Line= 2
     2057719.226       177209.78     2058345.418      177617.971
#Sta/Elev= 30
       01960.851  59.5551936.301 114.3841912.484 152.7651891.657 226.7351843.979
 236.8761835.869 247.5391823.169 266.9161806.264 290.9471788.534 300.2321782.603
 308.9711780.449 365.0291781.523 376.7781779.397 392.4441778.955  399.091779.584
 408.1091781.359 427.6911782.617 451.1891785.921 501.7551788.693 519.2481786.627
 537.2721790.336 588.2611795.806 609.3671800.748 632.1531801.199 639.4071800.418
 651.4231806.293  674.421814.064 693.4781822.282 729.5261836.109 747.4871841.062
#Mann= 5 ,-1 , 0
       0      .1       0 376.778    .045       0  399.09      .1       0
     520     .04       0     650      .1       0
#XS Ineff= 2 , 0
          308.04 1783.91
Permanent Ineff=
       F       F
Bank Sta=376.778,399.09
XS Rating Curve= 0 ,0
Exp/Cntr=0.3,0.1

Type RM Length L Ch R = 1 ,6970    ,419.5,440.4,433.5
XS GIS Cut Line= 4
     2057678.392      177241.6852057818.04652999177451.533549941
 2058005.3873871177626.9515400942058237.03967014177796.183359924
#Sta/Elev= 30
       01967.323  51.2421948.639  67.0961941.763 124.9391906.883 152.5251886.752
 173.5761869.137  190.141857.431 240.7381813.711 279.6271777.477 284.4271775.866
 303.6271777.379 332.4271774.989 346.8281777.878 366.0281778.636 411.8291778.815
 421.1141777.577 442.8291778.644 451.2881777.606  476.431777.979 481.6821779.974
  495.391781.621 556.2811795.041 570.3681799.252 591.4991799.533 603.2381805.722
 638.6741813.591 680.7171824.826 695.5571830.266 736.1881848.659 795.6021873.662
#Mann= 5 ,-1 , 0
       0      .1       0 451.288    .045       0  476.43      .1       0
  568.72     .04       0  698.72      .1       0
#XS Ineff= 2 , 0
          310.89 1791.77
Permanent Ineff=
       F       F
Bank Sta=451.288,476.43
XS Rating Curve= 0 ,0
Exp/Cntr=0.3,0.1

Type RM Length L Ch R = 1 ,6530    ,199.3,197.1,193.4
XS GIS Cut Line= 2
     2057373.165      177451.898     2057862.348      178001.062
#Sta/Elev= 30
       01982.764  29.1291966.501  51.0971949.559  64.2781942.573  90.641 1925.04
 102.0351918.695 133.1891896.923 166.1571877.389 195.9311856.461 257.6021822.159
 279.5861808.908   300.5 1791.98 319.115  1779.4 338.7931773.047 358.5231771.856
 377.1851770.075  386.481772.038 422.6451772.751 437.4431776.429  490.471780.271
 550.889 1788.39 573.9511793.743 590.9711801.173 610.0791801.022 622.2821807.424
 634.7411810.467 690.8931820.421 702.5121821.299 710.1561823.724 735.4461828.199
#Mann= 5 ,-1 , 0
       0      .1       0 358.523    .045       0  386.48      .1       0
     550     .04       0     680      .1       0
#XS Ineff= 2 , 0
                          398.78         1776.18
Permanent Ineff=
       F       F
Bank Sta=358.523,386.48
XS Rating Curve= 0 ,0
Exp/Cntr=0.3,0.1