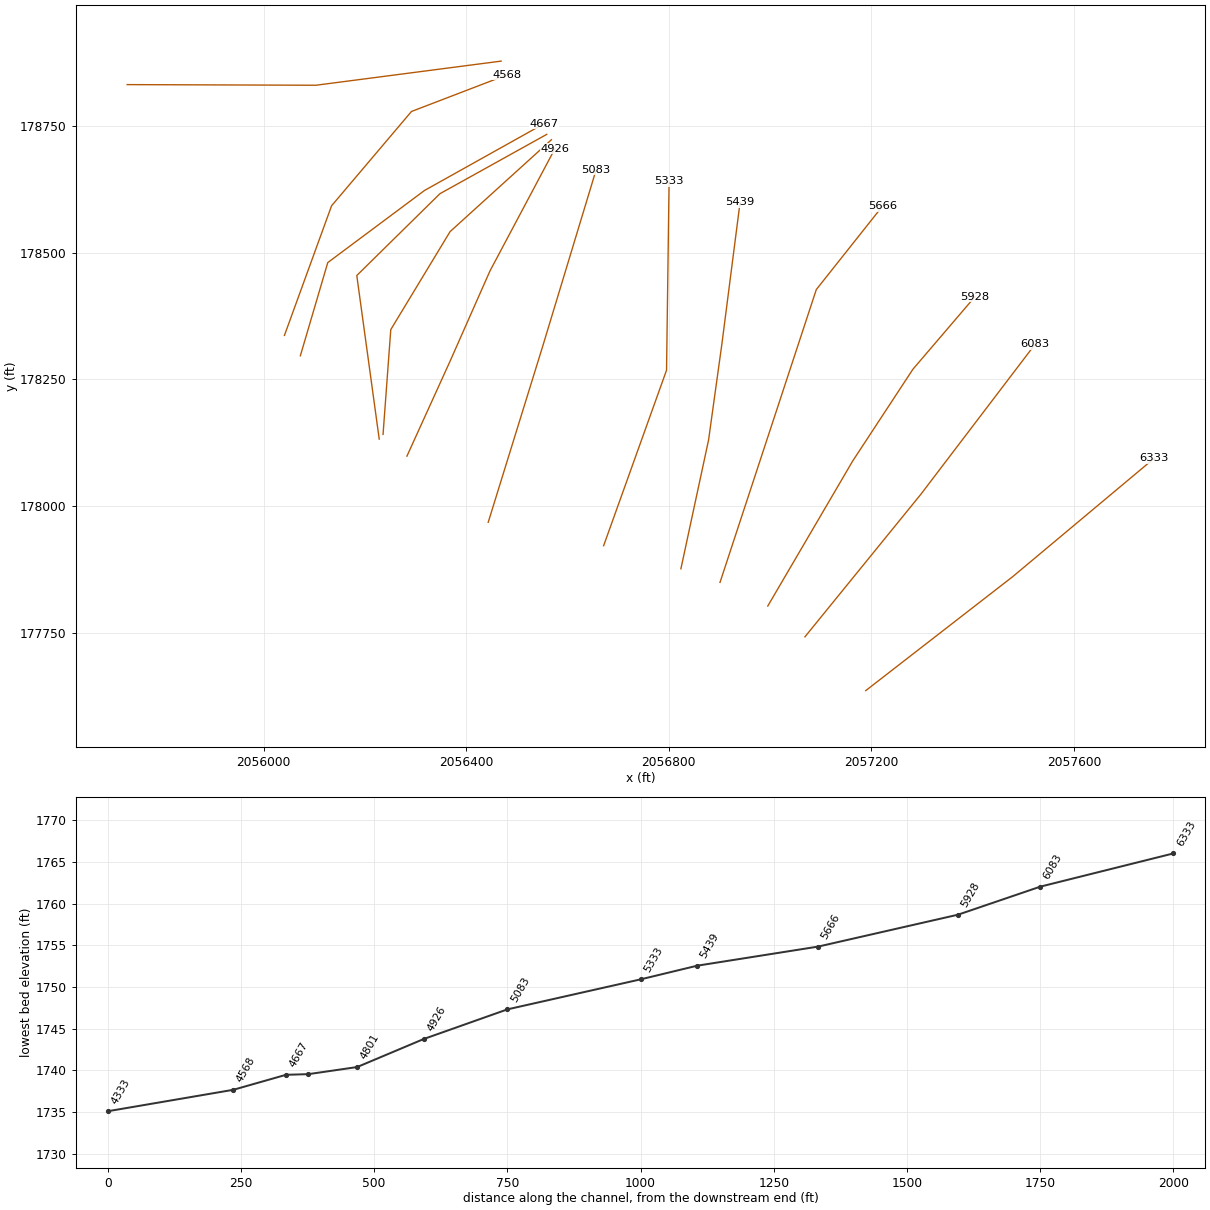
HEC-RAS study BLLKCK.prj: BLLKCK

--- BLLKCK.g01 (geometry) --- (continued)

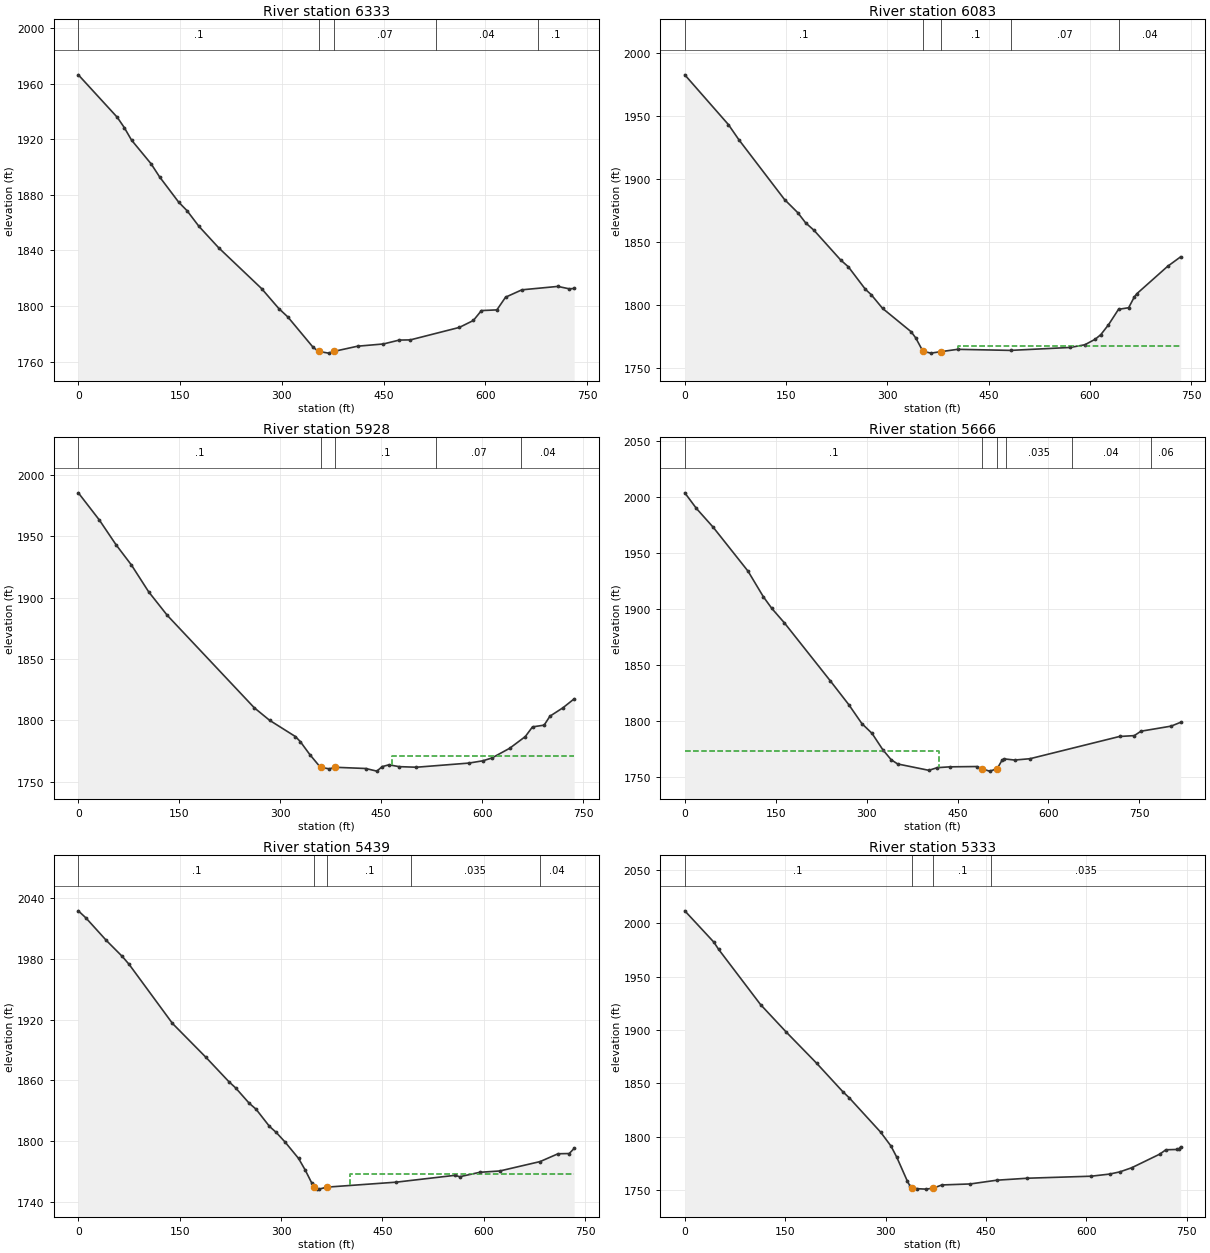
Type RM Length L Ch R = 1 ,6333    ,245.3,250,253.2
XS GIS Cut Line= 3
     2057188.947      177635.549      2057479.26      177860.674
     2057758.099      178093.941
#Sta/Elev= 30
       0 1966.58    57.3 1936.03    67.7  1928.6    78.4 1919.56   107.3 1902.44
   119.7  1893.1     148 1874.78   160.2 1868.71   177.8  1857.4   206.9 1841.95
   270.1 1812.58   295.8 1798.01   308.7 1792.19   346.1 1770.23   354.2 1767.27
   368.9 1766.04   377.21767.326   411.6 1771.03   449.8 1772.65   473.1 1775.45
   489.4 1775.58   561.6 1784.56   582.3 1789.56   594.2  1796.7     617  1797.2
   629.8 1806.35   653.9 1811.66   706.8 1814.11   723.9 1812.36   730.9 1812.66
#Mann= 5 ,-1 , 0
       0      .1       0   354.2    .045       0   377.2     .07       0
  527.37     .04       0  677.37      .1       0
Bank Sta=354.2,377.2
XS Rating Curve= 0 ,0
Exp/Cntr=0.3,0.1

Type RM Length L Ch R = 1 ,6083    ,150.5,154.2,153.7
XS GIS Cut Line= 3
     2057068.883      177741.737     2057297.666      178023.047
     2057523.011      178319.007
#Sta/Elev= 30
       0 1982.59    64.6 1943.17    80.2  1931.1   147.8 1883.75   167.3  1873.4
     179 1865.31   191.5 1859.35     231 1835.81   242.3 1830.47   267.5 1812.67
   276.1 1808.43     293 1797.52   335.2 1779.06   342.2 1774.09   352.81763.491
   364.8 1762.05   378.91763.183   404.3 1765.06   482.6 1764.22     571 1766.55
   592.6 1768.66   608.1 1773.08   616.4 1776.74   627.7 1784.49   642.6 1796.77
   657.6 1798.03   665.9 1806.47   669.8 1809.17   715.3 1830.83   734.6 1838.36
#Mann= 5 ,-1 , 0
       0      .1       0   352.8    .045       0   378.9      .1       0
   482.6     .07       0   642.6     .04       0
#XS Ineff= 2 , 0
                          405.09         1767.96
Permanent Ineff=
       F       F
Bank Sta=352.8,378.9
XS Rating Curve= 0 ,0
Exp/Cntr=0.3,0.1

Type RM Length L Ch R = 1 ,5928    ,259.1,262.7,270
XS GIS Cut Line= 4
2056995.50025915177802.4898523462057163.23065137178088.950746915
2057281.96115372178269.8734171692057404.46087837178413.103864453
#Sta/Elev= 30
       0 1985.41    31.2 1963.29    56.1 1943.06      79 1926.54   104.5 1904.78
   132.2 1885.58   261.5 1810.28   284.3 1800.07   322.7 1786.82   329.9 1782.71
   344.1 1772.12   359.9  1761.7     373 1760.57     382 1761.82     427 1760.83
   443.6 1758.69   451.5 1762.35   461.6 1763.84   476.8 1762.34   502.5 1761.87
   580.5 1765.25   601.3 1767.12   614.5 1769.39     641 1777.31   664.2 1786.85
   674.9 1794.73   692.2 1796.16   700.8 1803.45   720.1 1810.27   736.8 1817.57
#Mann= 5 ,-1 , 0
       0      .1       0   359.9    .045       0     382      .1       0
  531.95     .07       0  658.36     .04       0
#XS Ineff= 2 , 0
                          466.48         1771.08
Permanent Ineff=
       F       F
Bank Sta=359.9,382
XS Rating Curve= 0 ,0
Exp/Cntr(USF)=0,0
Exp/Cntr=0.3,0.1

Type RM Length L Ch R = 1 ,5666    ,217.9,226.9,227.1
XS GIS Cut Line= 3
     2056901.181      177849.078     2057091.285      178427.203
     2057221.493      178591.265
#Sta/Elev= 30
       0 2003.38    19.2 1989.41    46.9 1972.61   104.3 1933.43   129.7 1910.49
   143.6 1900.14   164.3 1887.26   240.3 1835.31   270.6 1814.19   292.1 1797.33
   308.9 1788.58   326.6 1774.05   340.4 1765.07   351.2 1761.25   402.6 1755.59
   416.4 1757.94   437.1 1758.69     482 1758.97   490.81756.805   502.7 1754.86
  515.041756.796   523.5 1764.69   526.9 1765.79   544.2 1764.76   569.5 1765.95
   717.3 1785.81   741.6 1786.57   752.5  1790.5   802.3 1795.04     818 1798.46
#Mann= 6 ,-1 , 0
       0      .1       0   490.8    .045       0  515.04      .1       0
     530    .035       0  638.58     .04       0  768.58     .06       0
#XS Ineff= 2 , 0
          419.77 1772.94
Permanent Ineff=
       F       F
Bank Sta=490.8,515.04
XS Rating Curve= 0 ,0
Exp/Cntr=0.3,0.1

Type RM Length L Ch R = 1 ,5439    ,108.8,106.2,104.8
XS GIS Cut Line= 4
2056824.00064464177875.9896871372056878.65436795178130.412192181
2056905.03892403178320.7579181782056940.84653585178599.680368153
#Sta/Elev= 30
       0 2027.79    11.3 2020.73    41.5 1998.45      65  1982.7    75.1 1974.88
   139.3 1916.42     189 1882.79   222.7 1858.87   232.8 1852.63   252.9 1837.44
   262.9 1831.67   282.8 1814.61   292.9 1808.58     306 1799.05   325.9 1782.88
   335.8  1771.3   345.7 1758.16   349.1 1754.81   352.4 1752.82   355.7 1752.57
   368.5 1754.58   470.5 1759.47   557.6 1766.25   564.2 1764.81     594 1769.21
   623.7 1770.54   683.3 1779.83   709.7 1787.54   726.3 1787.77   733.6 1792.84
#Mann= 5 ,-1 , 0
       0      .1       0   349.1    .045       0   368.5      .1       0
  492.39    .035       0  682.39     .04       0
#XS Ineff= 2 , 0
                          402.29         1767.06
Permanent Ineff=
       F       F
Bank Sta=349.1,368.5
XS Rating Curve= 0 ,0
Exp/Cntr(USF)=0,0
Exp/Cntr=0.3,0.1

Type RM Length L Ch R = 1 ,5333    ,246.8,250,246.4
XS GIS Cut Line= 3
     2056671.459      177921.576     2056795.673      178268.112
     2056800.686      178640.714
#Sta/Elev= 30
       0 2011.54    43.5 1982.15    50.4 1975.57   113.2 1923.73   151.5 1898.05
   196.8 1868.94   236.1 1842.17   245.6  1836.5   292.6 1804.28     308 1791.32
   316.7 1780.84   332.7 1758.15   336.2  1754.2   338.8 1752.42   346.7 1751.34
   360.6 1750.93   371.4 1751.84     384 1754.84   426.7 1755.79   466.1 1759.29
     512 1761.15   607.1 1763.03   634.7 1765.03   649.8 1767.06   667.8 1770.97
   709.9 1783.79   718.7 1787.78   735.1 1788.06   738.4 1788.78   740.8 1790.49
#Mann= 4 ,-1 , 0
       0      .1       0   338.8    .045       0   371.4      .1       0
  458.13    .035       0
Bank Sta=338.8,371.4
XS Rating Curve= 0 ,0
Exp/Cntr=0.3,0.1

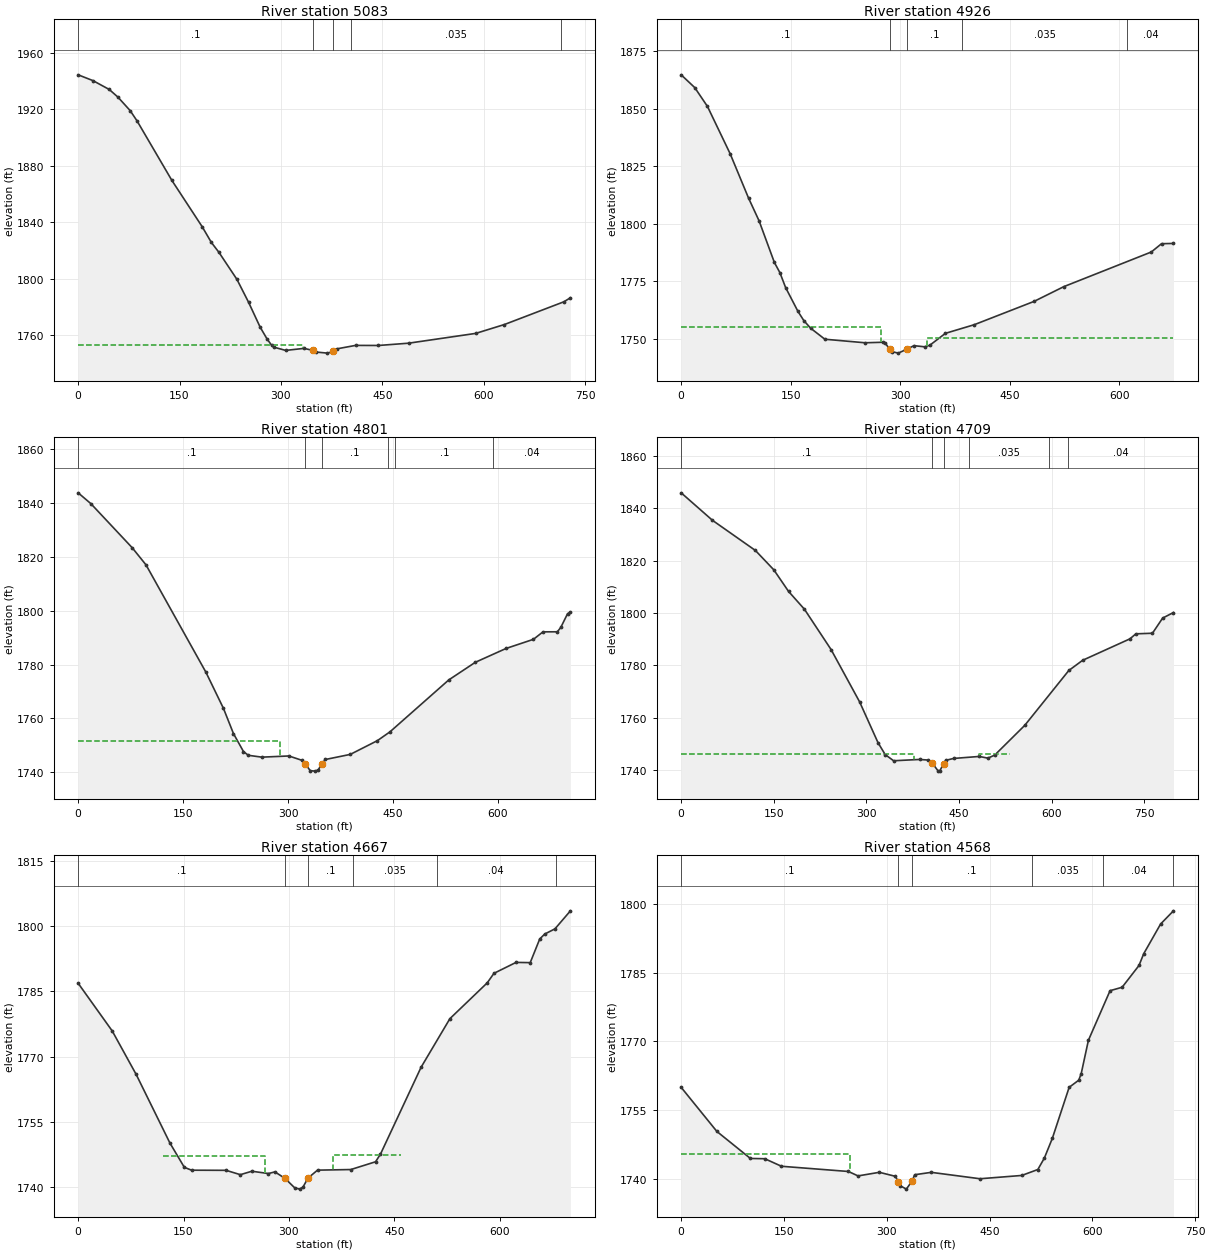
Type RM Length L Ch R = 1 ,5083    ,158.7,156.8,154.7
XS GIS Cut Line= 3
     2056443.605      177967.768     2056551.218      178315.453
     2056656.777      178664.057
#Sta/Elev= 30
       0 1944.22      22  1940.1      46 1933.86    58.8 1928.47    76.9 1918.92
    87.2 1911.56   138.7 1869.48   183.4 1836.81   197.1 1825.61   208.3  1818.6
   234.9 1799.49   252.1 1783.31   269.2 1765.73   279.5 1757.29   286.4 1752.77
   289.8 1751.51     307 1749.25   334.1 1750.69   347.61749.223   351.7 1748.11
   368.8 1747.33     3771748.602   382.5 1750.34   410.4  1752.8   444.2 1752.74
   488.8 1754.36   588.2  1761.3   630.5 1767.56   718.5 1783.65   728.2 1786.49
#Mann= 5 ,-1 , 0
       0      .1       0   347.6    .045       0     377      .1       0
  403.96    .035       0  713.96     .04       0
#XS Ineff= 2 , 0
          332.91 1752.76
Permanent Ineff=
       F       F
Bank Sta=347.6,377
XS Rating Curve= 0 ,0
Exp/Cntr=0.3,0.1

Type RM Length L Ch R = 1 ,4926    ,127,125.2,122.7
XS GIS Cut Line= 4
2056283.11724503178098.3738026572056367.92474671178284.950306357
2056447.07841495178463.9883654622056575.23197304178705.218592468
#Sta/Elev= 30
       0 1864.72    18.6 1859.17      36 1850.97      67 1830.46    92.2 1811.18
   106.6  1801.3   127.6 1783.18   135.1 1778.78     143 1772.26   159.9  1761.9
   167.9 1757.92   177.2 1754.62   196.7 1749.82   251.7 1748.28   275.7  1748.5
   279.3 1748.13  285.35 1745.55     289  1744.4   297.2 1743.78   308.9 1745.48
   318.7 1747.03   333.1 1746.53   340.2 1747.17   361.8 1752.39   401.2 1756.13
     483 1766.25   523.8 1772.67   643.6 1787.73   657.6 1791.33   673.9 1791.45
#Mann= 5 ,-1 , 0
       0      .1       0  285.35    .045       0   308.9      .1       0
  384.95    .035       0   610.7     .04       0
#XS Ineff= 2 , 0
          273.78  1755.1  337.05         1750.17
Permanent Ineff=
       F       F
Bank Sta=285.35,308.9
XS Rating Curve= 0 ,0
Exp/Cntr(USF)=0,0
Exp/Cntr=0.3,0.1

Type RM Length L Ch R = 1 ,4801    ,96,91.5,88.3
XS GIS Cut Line= 4
2056236.00214704178141.3046390282056251.26749734178348.234943132
2056368.30184966178541.5960469672056568.44755363178723.084100566
#Sta/Elev= 30
       0 1843.75    18.1 1839.75    77.3 1823.35      97    1817   182.6 1777.15
   207.7 1763.71     222 1754.36   236.3 1747.69   243.2 1746.29   262.6  1745.6
   301.2 1746.04   319.3 1744.48   324.7 1743.08   331.8 1740.57     339 1740.41
   343.3 1740.88     3481743.051   353.4 1744.73     389 1746.62   427.7 1751.72
   445.7 1754.99   529.8 1774.28   567.8 1780.83   611.7 1785.96   650.8 1789.35
   664.5 1792.13     685 1792.15   689.9 1793.76   699.6 1798.86   703.7 1799.45
#Mann= 6 ,-1 , 0
       0      .1       0   324.7    .045       0     348      .1       0
  443.51    .035       0  453.51      .1       0  593.51     .04       0
#XS Ineff= 2 , 0
          288.83 1751.53
Permanent Ineff=
       F       F
Bank Sta=324.7,348
XS Rating Curve= 0 ,0
Exp/Cntr(USF)=0,0
Exp/Cntr=0.5,0.3

Type RM Length L Ch R = 1 ,4709    ,45.2,42,41
XS GIS Cut Line= 4
     2056228.438      178132.064     2056184.167       178454.98
      2056348.23      178616.439     2056559.167      178733.626
#Sta/Elev= 30
       0 1845.92    50.7 1835.41   120.3 1823.88   150.1 1816.48   173.9 1808.26
   199.7 1801.42   242.8 1786.03   289.1    1766   318.9 1750.41   330.5 1745.88
   344.1 1743.52   386.2 1744.02   400.3 1743.79     4071742.548   416.4 1739.56
     419 1739.72  425.311742.446   428.3 1743.67   441.4 1744.41   482.9 1745.17
   496.7 1744.53   507.8 1745.66   556.5 1757.04   627.9 1778.02   650.3 1781.92
   726.9 1790.11   736.5 1792.03   763.4 1792.26   779.9 1798.05   797.4 1800.17
#Mann= 6 ,-1 , 0
       0      .1       0     407    .045       0  425.31      .1       0
  465.94    .035       0  596.12      .1       0  626.12     .04       0
#XS Ineff= 4 ,-1
       0  377.12 1745.95  387.62  398.461742.718  433.64  445.181742.789
  482.31  533.03 1746.28
Permanent Ineff=
       F       F       F       F
Bank Sta=407,425.31
XS Rating Curve= 0 ,0
Exp/Cntr=0.5,0.3

Type RM Length L Ch R = 1 ,4667    ,95.8,99,101.4
XS GIS Cut Line= 4
2056072.73392795178296.501258062     2056126.875      178480.501
     2056317.848      178622.862     2056553.959      178754.807
#Sta/Elev= 30
       0 1786.89    48.5  1775.9    82.6 1765.88   130.6 1750.09   151.1  1744.5
   161.4 1743.84   210.4 1743.81   230.8 1742.81   247.2  1743.6   270.7 1743.07
     280 1743.45 294.1751741.973   308.2 1739.77   315.3 1739.48     320 1739.96
 326.997 1742.02   340.6 1743.85     388 1743.99   423.2 1745.78   430.2 1747.54
     488 1767.55     529 1778.74   582.1 1786.98   591.7 1789.18   623.1 1791.69
   643.3 1791.64   656.8 1797.08     664 1798.23   678.5 1799.42   700.5 1803.57
#Mann= 6 ,-1 , 0
       0      .1       0 294.175    .045       0 326.997      .1       0
   391.8    .035       0     510     .04       0     680      .1       0
#XS Ineff= 4 ,-1
  120.34   265.9  1747.1  282.79  291.32 1742.01  329.41  339.48 1742.03
  362.18   459.6 1747.25
Permanent Ineff=
       F       F       F       F
Bank Sta=294.175,326.997
XS Rating Curve= 0 ,0
Exp/Cntr=0.5,0.3

Type RM Length L Ch R = 1 ,4568    ,250,235.5,224.3
XS GIS Cut Line= 4
2056041.32437896178336.7181716072056134.39159617178592.653018932
2056292.08882533 178778.787453352056480.80846023178851.173066735
#Sta/Elev= 30
       0 1759.94    52.1  1750.3     101 1744.39     122 1744.33   146.4 1742.68
   244.1 1741.54   258.1 1740.57   289.2 1741.36   312.4 1740.49     317 1739.33
   319.3 1738.46   328.6 1737.68  336.55 1739.37   340.8 1740.83     365 1741.35
   436.1 1739.95     497 1740.67   520.5 1741.97     530 1744.47   541.6 1748.76
   566.2 1759.95   580.2 1761.51   583.8 1762.95   594.3 1770.24   625.9 1781.09
   643.5 1781.84   668.1  1786.6   675.1  1789.2   699.7 1795.68   718.4 1798.56
#Mann= 6 ,-1 , 0
       0      .1       0     317    .045       0  336.55      .1       0
  512.33    .035       0  616.29     .04       0  718.41      .1       0
#XS Ineff= 2 , 0
          246.42 1745.37
Permanent Ineff=
       F       F
Bank Sta=317,336.55
XS Rating Curve= 0 ,0
Exp/Cntr(USF)=0,0
Exp/Cntr=0.3,0.1

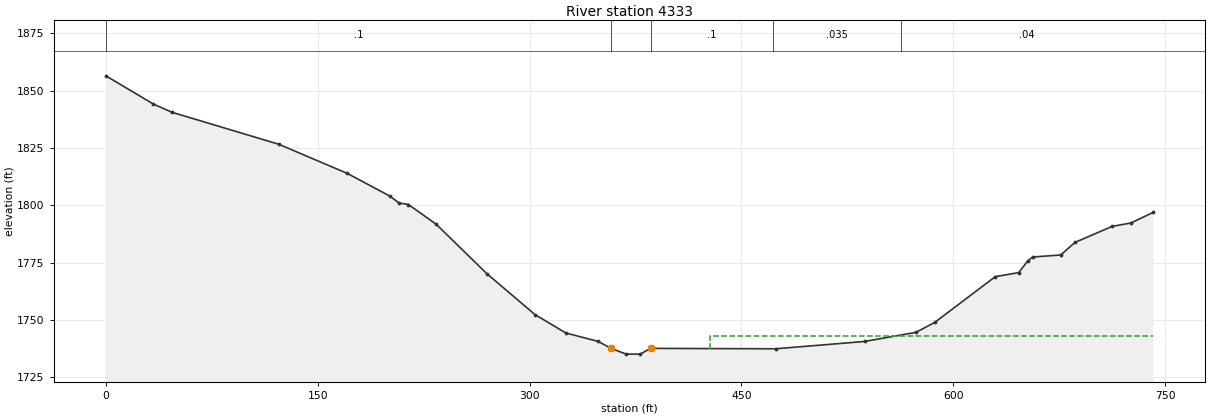
Type RM Length L Ch R = 1 ,4333    ,240,250,253.1
XS GIS Cut Line= 3
     2055730.802      178831.857     2056103.463      178830.587
     2056469.076      178878.236
#Sta/Elev= 30
       0 1856.47    33.7 1844.13    46.8 1840.57   122.3 1826.65   170.9 1813.93
     201 1804.04   207.6 1801.01   214.2 1800.35   233.9 1791.73   269.9  1770.1
   303.8 1752.36   325.7 1744.31   348.7 1740.64  357.351737.674   368.4 1735.11
   378.3 1735.12   385.71737.616   474.2 1737.44   537.1 1740.63   573.5  1744.6
   586.8 1748.93   629.7 1768.89   646.3 1770.66   652.9 1775.91   656.2 1777.47
     676 1778.34   686.1 1783.82   712.4 1790.81   725.7  1792.3   741.4 1796.88
#Mann= 5 ,-1 , 0
       0      .1       0  357.35    .045       0   385.7      .1       0
  472.66    .035       0  562.66     .04       0
#XS Ineff= 2 , 0
                          427.51         1743.06
Permanent Ineff=
       F       F
Bank Sta=357.35,385.7
XS Rating Curve= 0 ,0
Exp/Cntr=0.3,0.1