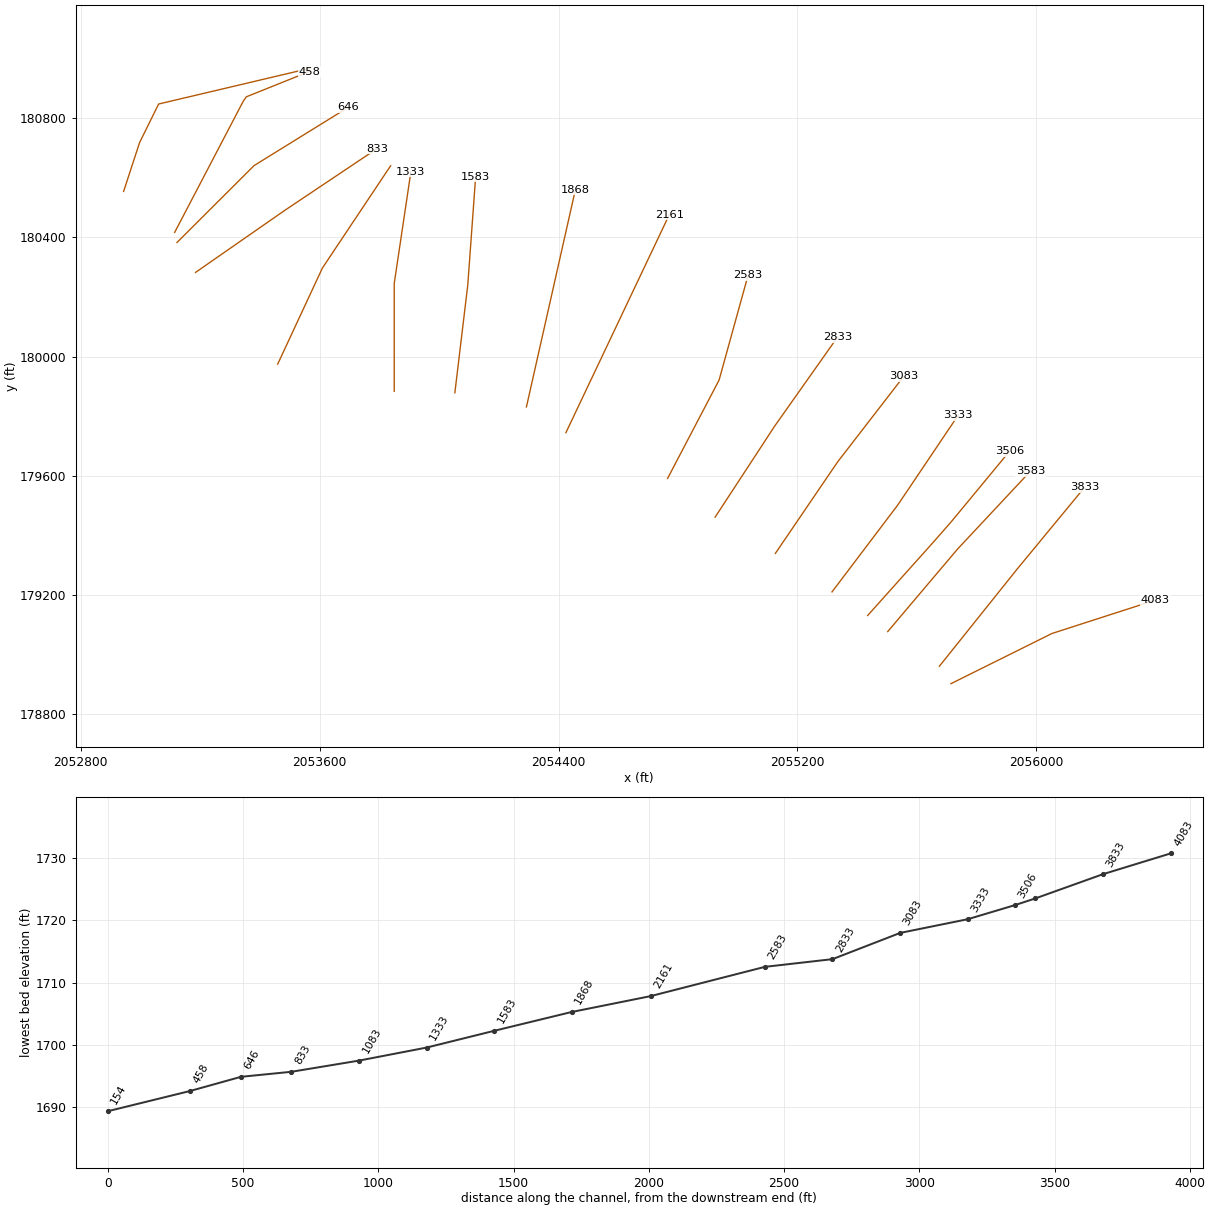
HEC-RAS study BLLKCK.prj: BLLKCK

--- BLLKCK.g01 (geometry) --- (continued)

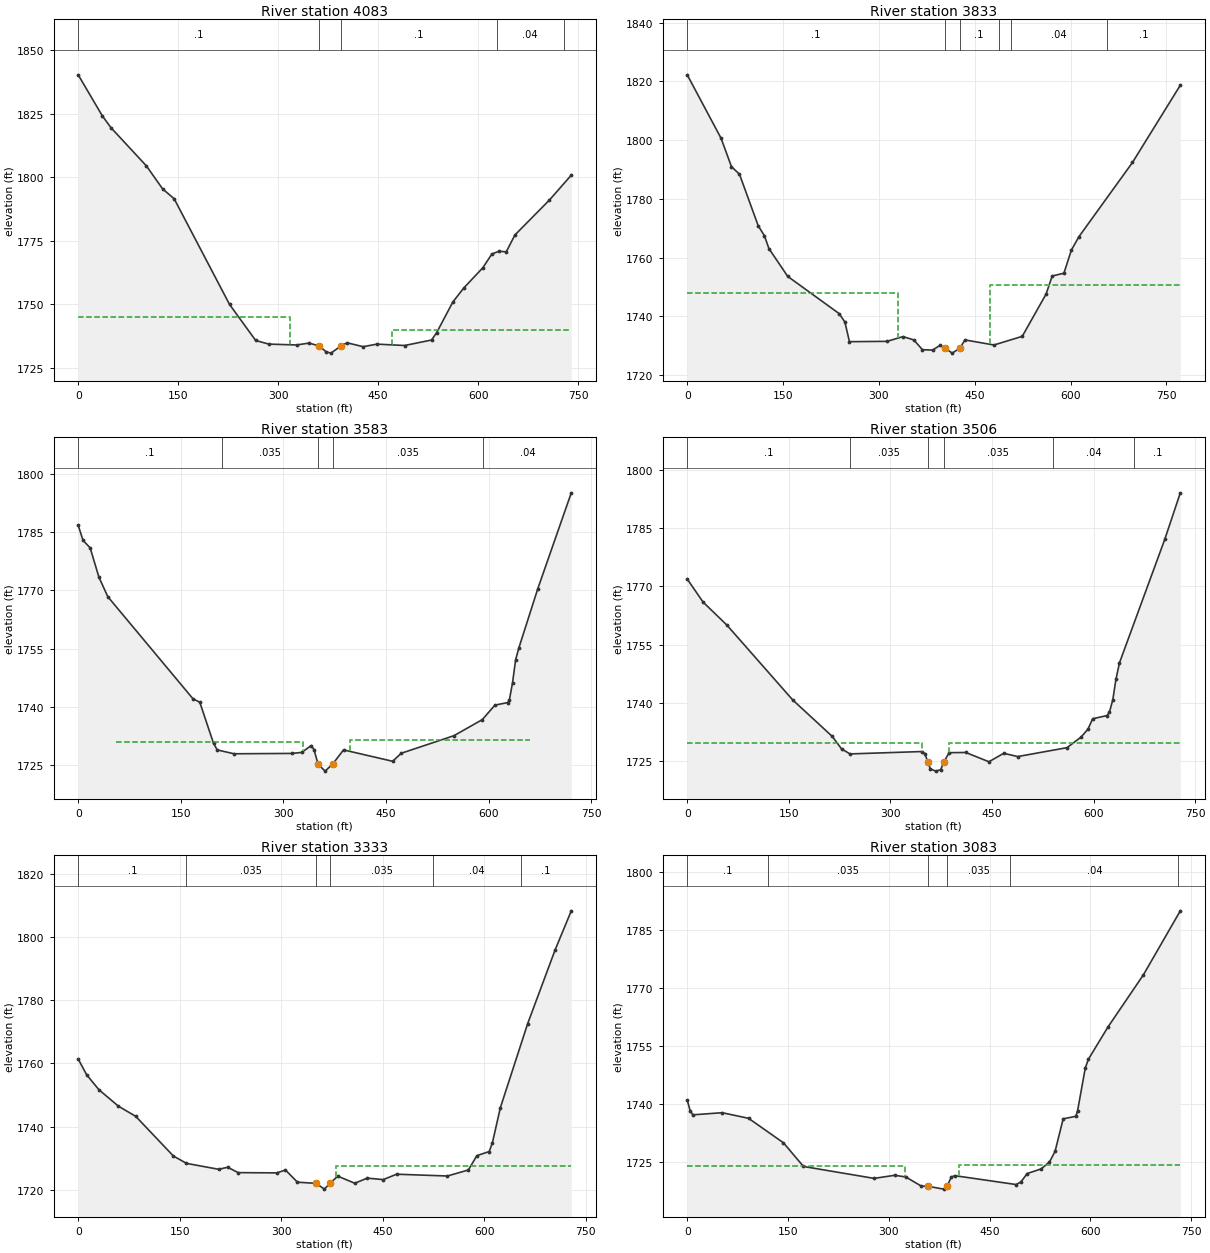
Type RM Length L Ch R = 1 ,4083    ,237.2,250,259.2
XS GIS Cut Line= 3
     2055713.798      178903.016     2056052.124      179071.435
     2056396.186      179182.595
#Sta/Elev= 30
       0 1840.26    36.2 1824.11    49.3 1819.42   102.3 1804.43   126.7 1795.36
   143.9 1791.52     227 1749.93   266.2 1735.76   285.8 1734.33   327.4 1733.99
   346.2 1734.72   361.6 1733.61   371.8  1731.3   379.1 1730.78   394.21733.639
   403.2 1734.85   427.4 1733.31   448.1 1734.32   489.4 1733.78   529.9 1735.93
   537.6 1738.85   561.8 1750.85   578.3 1756.42   606.7 1764.32   620.4 1769.76
   630.8 1770.84     642 1770.65     655 1777.27   706.6 1790.97   739.5 1800.79
#Mann= 5 ,-1 , 0
       0      .1       0   361.6    .045       0   394.2      .1       0
  627.93     .04       0  727.93      .1       0
#XS Ineff= 2 , 0
          317.25    1745  469.91         1740.04
Permanent Ineff=
       F       F
Bank Sta=361.6,394.2
XS Rating Curve= 0 ,0
Exp/Cntr=0.3,0.1

Type RM Length L Ch R = 1 ,3833    ,236.8,250,242.9
XS GIS Cut Line= 3
     2055675.167      178961.609     2055935.681      179287.694
     2056160.987      179561.285
#Sta/Elev= 30
       0 1822.24      53 1800.62    69.2 1790.98    81.8 1788.37   111.1 1770.83
   120.7 1767.49   127.9 1763.05   157.3 1753.58   237.8  1740.9   246.8 1738.03
   253.9 1731.34   312.7 1731.45   337.8 1733.07   354.7 1731.94   368.1 1728.62
   384.1 1728.47   395.5 1730.06   403.2 1729.21   414.8 1727.44   426.8 1729.16
   434.7 1731.94   480.1 1730.21   524.4 1733.16   561.7 1747.56   571.3 1753.72
   589.6 1754.66   601.3 1762.53   612.9 1767.04   696.9 1792.38   771.8  1818.7
#Mann= 6 ,-1 , 0
       0      .1       0   403.2    .045       0   426.8      .1       0
  487.37    .035       0  507.37     .04       0  657.37      .1       0
#XS Ineff= 2 , 0
           329.9 1748.05   473.4         1750.78
Permanent Ineff=
       F       F
Bank Sta=403.2,426.8
XS Rating Curve= 0 ,0
Exp/Cntr=0.5,0.3

Type RM Length L Ch R = 1 ,3583    ,76.6,76.2,76.8
XS GIS Cut Line= 3
      2055502.16      179077.723     2055736.045      179354.691
2055980.62910633179616.610828107
#Sta/Elev= 30
       0 1786.72     7.1 1782.87    17.5 1780.92    30.4 1773.35    43.3 1768.38
   167.7 1742.16   177.8 1741.23   197.9 1730.67   203.3 1728.99   227.9    1728
   312.1 1728.09   326.7 1728.34   340.6 1730.12   344.7 1729.09   350.7 1725.33
     361 1723.54   372.6 1725.47   387.9    1729   459.7 1726.07   472.4 1728.14
   549.5 1732.66   590.8 1736.78   609.3 1740.51   627.9 1741.16   630.3 1741.76
     635 1746.24   639.5 1752.13   644.2 1755.18     672 1770.46   720.9 1795.08
#Mann= 5 ,-1 , 0
       0      .1       0     210    .035       0   350.7    .045       0
   372.6    .035       0  592.51     .04       0
#XS Ineff= 2 ,-1
   55.01  329.331731.117  396.78  660.131731.556
Permanent Ineff=
       F       F
Bank Sta=350.7,372.6
XS Rating Curve= 0 ,0
Exp/Cntr=0.5,0.3

Type RM Length L Ch R = 1 ,3506    ,172.8,173.8,176.3
XS GIS Cut Line= 4
2055434.95918276179131.6781948552055654.83774747179377.704480775
2055714.26438658179445.4508493622055910.37229565179683.157405806
#Sta/Elev= 30
       0 1771.89    23.4 1765.96    58.3 1760.09   155.9 1740.75     214 1731.42
   227.9 1728.17   240.4 1726.88   346.4 1727.49   351.1 1726.96  355.081724.825
     359 1723.05   366.9 1722.45   374.3 1722.81     379 1724.82   386.8  1727.2
   411.3 1727.25   445.6 1724.86   467.4 1727.04   488.1  1726.2   560.9 1728.49
   581.6 1731.21   591.9 1733.27   598.7 1735.93     620 1736.75   623.6 1737.65
   628.5 1740.82   633.1 1746.05   638.3 1750.29   705.3 1782.14   728.2 1794.08
#Mann= 6 ,-1 , 0
       0      .1       0     240    .035       0  355.08    .045       0
     379    .035       0  540.08     .04       0  660.08      .1       0
#XS Ineff= 2 , 0
          347.28 1729.57  386.25         1729.73
Permanent Ineff=
       F       F
Bank Sta=355.08,379
XS Rating Curve= 0 ,0
Exp/Cntr(USF)=0,0
Exp/Cntr=0.5,0.3

Type RM Length L Ch R = 1 ,3333    ,248.8,250,248.6
XS GIS Cut Line= 3
     2055315.613      179210.925     2055534.973      179501.253
     2055738.371      179803.941
#Sta/Elev= 30
       0 1761.35    12.4 1756.39    30.7 1751.62    59.5 1746.42      85 1743.22
   140.6 1730.68     160 1728.34   207.6 1726.46   220.9 1727.11   236.3 1725.41
   293.5 1725.33   306.3 1726.23     324 1722.38   351.5 1722.02   363.8 1720.19
  372.55 1722.15   383.6 1724.29   408.7 1722.05   427.1 1723.67   450.8  1723.2
   470.5 1724.91   545.6 1724.34   576.5 1726.25   589.1 1730.78   607.3 1732.08
     612 1734.81   623.8 1745.95   664.2 1772.57   704.9 1795.97   728.6 1808.23
#Mann= 6 ,-1 , 0
       0      .1       0     160    .035       0   351.5    .045       0
  372.55    .035       0  523.88     .04       0  653.88      .1       0
#XS Ineff= 2 , 0
                          381.66         1727.45
Permanent Ineff=
       F       F
Bank Sta=351.5,372.55
XS Rating Curve= 0 ,0
Exp/Cntr=0.3,0.1

Type RM Length L Ch R = 1 ,3083    ,248.7,250,249.8
XS GIS Cut Line= 3
     2055125.976      179340.107     2055334.448      179647.006
     2055556.026      179934.235
#Sta/Elev= 30
       0 1740.99     4.4 1738.26     8.3 1737.19      52 1737.74    91.3 1736.29
   143.2 1729.96     173 1723.84   278.1 1720.76   308.8 1721.56   325.3 1721.12
   348.2 1718.78     3581718.724   381.6 1717.98   386.6 1718.68     393 1721.11
   398.2 1721.46   489.3 1719.17   496.5 1719.82   505.9    1722   526.6 1723.21
   539.1 1724.98   547.4 1727.74   559.5 1736.16   578.4 1736.81     581 1738.31
   592.4 1749.31   597.1 1751.59   626.1 1759.89     679 1773.43   733.8 1789.94
#Mann= 6 ,-1 , 0
       0      .1       0     120    .035       0     358    .045       0
   386.6    .035       0  481.01     .04       0  731.01      .1       0
#XS Ineff= 2 , 0
          324.36 1723.96  404.58         1724.27
Permanent Ineff=
       F       F
Bank Sta=358,386.6
XS Rating Curve= 0 ,0
Exp/Cntr=0.3,0.1

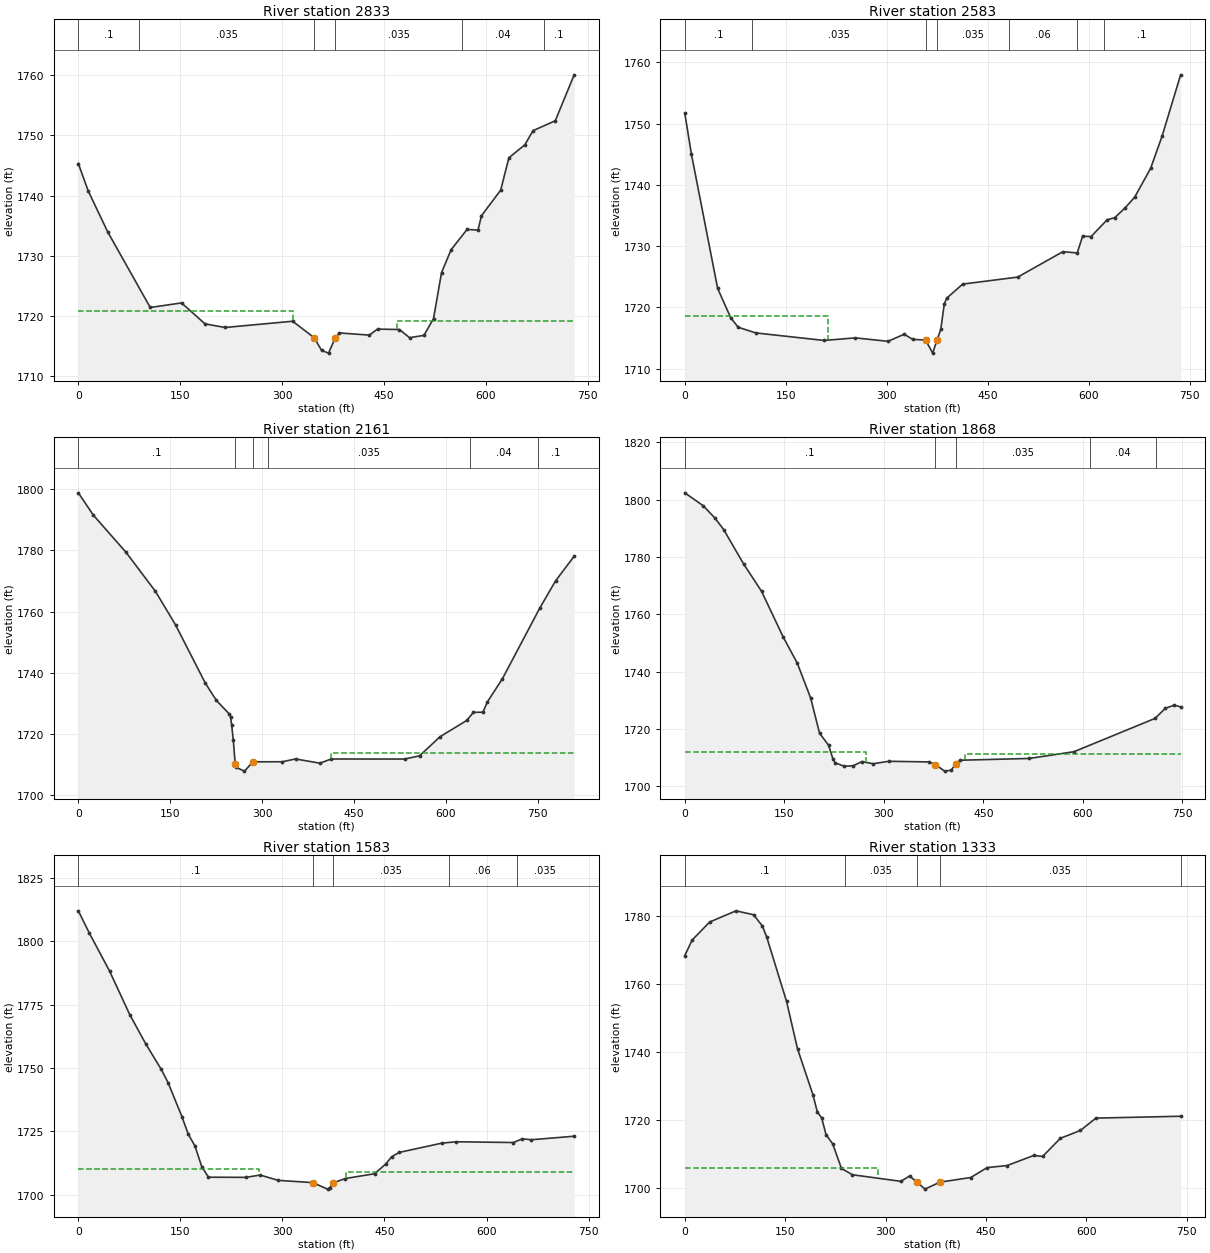
Type RM Length L Ch R = 1 ,2833    ,248,250,250.7
XS GIS Cut Line= 3
     2054924.326       179461.74     2055124.036      179767.618
     2055334.367      180065.856
#Sta/Elev= 30
       0 1745.32    14.5 1740.78    43.2 1733.96   105.9 1721.36     152 1722.12
   186.6 1718.63     216 1718.03   315.6 1719.07  347.311716.328   358.2 1714.22
   368.5 1713.76   378.31716.292   384.6 1717.12   428.7 1716.76   440.6 1717.76
   472.9 1717.69   487.8 1716.33     509 1716.72   523.1 1719.52   534.9 1727.17
     549 1730.98   572.5 1734.36   588.6 1734.24   593.7 1736.64     622  1740.9
   634.1 1746.29   657.6 1748.45   669.6  1750.8   702.4 1752.45   730.2  1760.1
#Mann= 6 ,-1 , 0
       0      .1       0      90    .035       0  347.31    .045       0
   378.3    .035       0   565.3     .04       0   685.3      .1       0
#XS Ineff= 2 , 0
          316.33 1720.71  469.25          1719.1
Permanent Ineff=
       F       F
Bank Sta=347.31,378.3
XS Rating Curve= 0 ,0
Exp/Cntr=0.3,0.1

Type RM Length L Ch R = 1 ,2583    ,417,422.1,413
XS GIS Cut Line= 3
     2054765.072      179591.566     2054937.507      179921.382
     2055034.478      180272.583
#Sta/Elev= 30
       0 1751.68     9.9 1744.96    48.8 1723.08    68.3 1718.27    79.4 1716.74
   105.4 1715.82   206.9 1714.59   253.4 1715.01   301.9 1714.45     326 1715.61
   338.6 1714.75   357.6 1714.67   368.2 1712.52   374.9 1714.73   380.2 1716.38
   385.4 1720.51   388.9 1721.48   412.8 1723.79   494.5 1724.93   561.6 1729.08
   582.9 1728.87   590.9 1731.62   603.4 1731.54   627.2 1734.27   638.9 1734.65
   654.4 1736.27   668.2 1737.98   691.9 1742.67   708.9 1747.92   736.5 1757.95
#Mann= 7 ,-1 , 0
       0      .1       0     100    .035       0   357.6    .045       0
   374.9    .035       0  482.17     .06       0  582.17     .04       0
  622.17      .1       0
#XS Ineff= 2 , 0
          212.18 1718.53
Permanent Ineff=
       F       F
Bank Sta=357.6,374.9
XS Rating Curve= 0 ,0
Exp/Cntr=0.3,0.1

Type RM Length L Ch R = 1 ,2161    ,275.8,292.4,290.4
XS GIS Cut Line= 2
     2054424.618      179744.911     2054770.973      180476.682
#Sta/Elev= 30
       0 1798.82    24.4 1791.55      78 1779.34     126 1766.57   158.7 1755.65
   207.3  1736.6   225.5 1730.91   246.7 1726.45   248.5 1725.61   250.3 1722.99
   253.1 1717.84   256.11710.262   256.7 1709.12   271.3 1707.81   285.21710.855
     333 1710.88   354.7 1711.79   394.6  1710.4   412.8 1711.78   532.6 1711.76
   557.1 1712.81   590.6 1719.06   634.2 1724.39   645.1 1727.04   660.6 1727.07
     668 1730.48   692.3 1737.97   753.3 1761.08   779.4 1770.08   809.6 1778.09
#Mann= 6 ,-1 , 0
       0      .1       0   256.1    .045       0   285.2      .1       0
     310    .035       0     640     .04       0     750      .1       0
#XS Ineff= 2 , 0
                           412.8         1713.69
Permanent Ineff=
       F       F
Bank Sta=256.1,285.2
XS Rating Curve= 0 ,0
Exp/Cntr=0.3,0.1

Type RM Length L Ch R = 1 ,1868    ,281.4,285.5,287.6
XS GIS Cut Line= 2
2054292.44883456179831.2433358462054456.45802004180560.233616544
#Sta/Elev= 30
       01802.392  27.7111797.894  45.0741793.676  58.5261789.589  88.7911777.508
 115.6941768.016 148.5011751.964 169.4991742.952 189.6761730.765 203.128 1718.45
 216.5791714.331 223.3051709.505 226.6681708.172 240.1191706.954  253.571707.105
 267.0221708.595 283.8361707.825 307.3761708.681 367.9071708.465   377.8 1707.54
 391.447 1705.25 401.5351705.575 408.2611707.813 414.9871709.051 519.2351709.676
 586.4921712.027 708.525 1723.64 724.368  1727.2 737.8191728.292 747.2121727.687
#Mann= 5 ,-1 , 0
       0      .1       0   377.8    .045       0 408.261    .035       0
     610     .04       0     710    .035       0
#XS Ineff= 2 , 0
          272.45 1711.96  422.23         1711.39
Permanent Ineff=
       F       F
Bank Sta=377.8,408.261
XS Rating Curve= 0 ,0
Exp/Cntr=0.3,0.1

Type RM Length L Ch R = 1 ,1583    ,246.2,250,247
XS GIS Cut Line= 3
     2054052.863       179878.87     2054096.104      180240.423
     2054122.507      180604.175
#Sta/Elev= 30
       0 1812.06    16.1  1803.3    45.9  1788.3    75.6 1771.09    98.8  1759.7
   121.9 1749.47   131.8 1744.31   152.3 1730.83   161.5 1723.97   171.4 1719.27
   181.4 1711.11   191.3 1706.93   246.7 1706.88   267.3 1707.79   293.7 1705.69
   344.4 1704.81   366.4 1702.23   369.7 1702.81   373.91704.646   392.7 1706.42
   435.5 1708.31   451.9 1712.16   460.4 1714.97   471.6 1716.71   534.1 1720.37
     555 1720.92   639.4 1720.62   652.6  1722.1   665.7 1721.71   728.8 1723.11
#Mann= 5 ,-1 , 0
       0      .1       0   344.4    .045       0   373.9    .035       0
  544.13     .06       0  644.13    .035       0
#XS Ineff= 2 , 0
          265.84 1710.14  393.62         1709.05
Permanent Ineff=
       F       F
Bank Sta=344.4,373.9
XS Rating Curve= 0 ,0
Exp/Cntr=0.3,0.1

Type RM Length L Ch R = 1 ,1333    ,256.9,250,237.8
XS GIS Cut Line= 3
     2053849.832      179883.985     2053849.832      180245.285
     2053905.691      180620.453
#Sta/Elev= 30
       0 1768.35    10.9 1772.93    37.2 1778.26    76.5 1781.55   102.8 1780.39
   115.9 1777.06   122.5 1773.74     152 1754.84   168.4 1740.87   191.4 1727.34
   197.9 1722.31   204.5 1720.48     211 1715.55   220.9 1712.89     234 1705.63
   250.4 1703.77   322.6 1701.83   335.7 1703.38  346.671701.642   358.7 1699.53
   380.9 1701.58   427.1 1702.95   451.5 1705.87   481.4 1706.48   521.2 1709.45
   534.5 1709.16     561 1714.51   590.8 1716.81   614.1 1720.46   740.6 1721.01
#Mann= 5 ,-1 , 0
       0      .1       0     240    .035       0  346.67    .045       0
   380.9    .035       0   740.6     .04       0
#XS Ineff= 2 , 0
           289.3 1705.73
Permanent Ineff=
       F       F
Bank Sta=346.67,380.9
XS Rating Curve= 0 ,0
Exp/Cntr=0.3,0.1

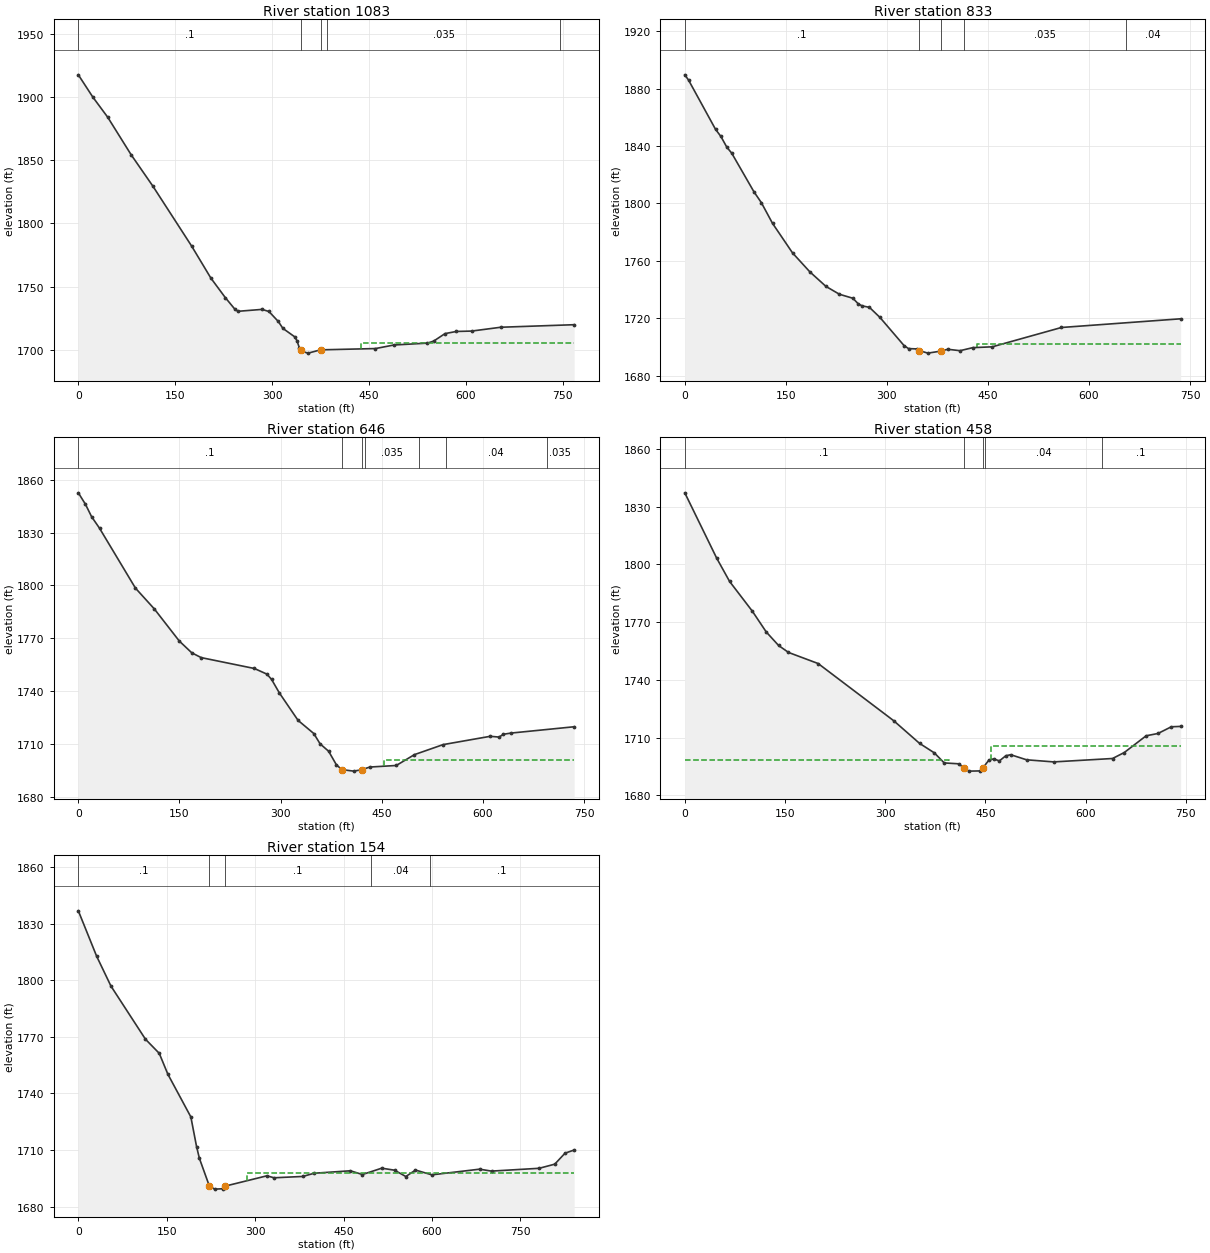
Type RM Length L Ch R = 1 ,1083    ,255.7,250,236.6
XS GIS Cut Line= 3
      2053459.71      179975.031     2053609.391       180297.38
     2053837.886      180640.506
#Sta/Elev= 30
       0 1917.35    22.4 1899.79    45.5 1883.84    81.7 1854.24   115.3 1829.47
   175.4 1782.05   205.2 1756.73   227.5 1741.34   242.3  1732.2   247.2 1730.48
   284.4 1731.99   295.1 1730.33   309.6 1722.45   316.8 1716.95   334.9 1710.36
   338.5 1707.28   342.1 1701.79  344.121700.102     346 1698.81   355.9 1697.43
     3751700.018     460 1701.04   488.4 1703.84   540.5 1705.33   550.1 1706.92
   567.8 1712.87   585.3 1714.55     609 1714.86     654 1717.88   767.7 1719.89
#Mann= 5 ,-1 , 0
       0      .1       0  344.12    .045       0     375      .1       0
  385.41    .035       0  745.41     .04       0
#XS Ineff= 1 ,-1
  436.95   767.6 1705.17
Permanent Ineff=
       F
Bank Sta=344.12,375
XS Rating Curve= 0 ,0
Exp/Cntr=0.3,0.1

Type RM Length L Ch R = 1 ,833     ,187.6,186.4,185.3
XS GIS Cut Line= 3
     2053184.465      180282.498     2053483.638      180490.895
     2053791.969      180697.683
#Sta/Elev= 30
       0 1889.72     5.6 1886.03    45.6 1851.73    53.6 1846.72    62.3  1839.3
    69.6 1835.12   102.5 1808.24   113.6  1800.6   130.2 1786.13   159.9 1765.53
   185.5 1752.37   209.5 1742.16   229.5 1736.69   249.5 1733.89   257.5 1729.97
   263.2  1728.6     274 1727.56   289.5  1720.6   325.5 1700.85   332.1 1698.79
   344.7 1698.56   348.31697.344   360.8 1695.63   380.91697.103   390.2 1698.32
   408.5 1697.33   427.4 1699.45   456.3 1700.03     559 1713.51   735.9 1719.57
#Mann= 5 ,-1 , 0
       0      .1       0   348.3    .045       0   380.9      .1       0
   414.6    .035       0   654.6     .04       0
#XS Ineff= 1 ,-1
  433.65   735.8 1702.26
Permanent Ineff=
       F
Bank Sta=348.3,380.9
XS Rating Curve= 0 ,0
Exp/Cntr=0.3,0.1

Type RM Length L Ch R = 1 ,646     ,173.5,187.9,194.3
XS GIS Cut Line= 3
     2053122.535      180382.932     2053380.348      180640.744
     2053695.452      180836.057
#Sta/Elev= 30
       0  1852.5    10.6 1845.99    19.7 1838.95    31.4 1832.46    84.7 1798.51
   112.7 1786.72   149.7 1768.54   168.3 1761.83   182.3 1759.13   261.1 1752.97
   279.7 1749.77   286.6 1746.77   298.1 1739.14   325.9 1723.56   349.2 1716.12
   358.5  1710.3   371.2 1706.08   382.7  1698.4   390.81695.664   408.4 1694.82
   420.41695.622   432.2 1697.13   471.5 1698.02   498.5 1704.18     541 1709.85
   610.9 1714.55   624.1 1714.11   630.3 1715.71   641.9 1716.39   735.3 1719.96
#Mann= 7 ,-1 , 0
       0      .1       0   390.8    .045       0   420.4      .1       0
   424.6    .035       0   504.6      .1       0   544.6     .04       0
   694.6    .035       0
#XS Ineff= 2 , 0
                          453.06         1701.09
Permanent Ineff=
       F       F
Bank Sta=390.8,420.4
XS Rating Curve= 0 ,0
Exp/Cntr=0.3,0.1

Type RM Length L Ch R = 1 ,458     ,294.4,304.7,294.4
XS GIS Cut Line= 4
     2053114.723      180416.7862053343.58845161180855.425980592
2053354.31533789180871.4843720872053565.86669178  180956.5190773
#Sta/Elev= 30
       0 1837.12    47.8 1803.13    67.1 1791.06   101.1 1775.63   121.9 1764.84
   140.4 1757.81   155.2  1754.2   199.6 1748.43   312.7 1718.72   351.3 1706.98
   373.5 1702.02   388.3  1696.8   410.5 1696.33  417.191694.173   425.3 1692.54
   441.6 1692.65 446.4531694.325   454.9 1698.18   462.3 1698.91   470.8 1697.85
   480.5 1700.54   487.8 1701.06   511.5 1698.43   552.2 1697.33   640.2  1699.1
   657.8 1702.21   690.5  1710.9   708.2  1712.1   728.2 1715.58   742.1 1715.77
#Mann= 5 ,-1 , 0
       0      .1       0  417.19    .045       0 446.453      .1       0
     450     .04       0  624.07      .1       0
#XS Ineff= 2 , 0
          395.14 1698.31  458.45         1705.41
Permanent Ineff=
       F       F
Bank Sta=417.19,446.453
XS Rating Curve= 0 ,0
Exp/Cntr=0.3,0.1

Type RM Length L Ch R = 1 ,154     ,,,
XS GIS Cut Line= 4
2052943.79860281180554.273421829 2052997.2626986  180718.1150057
2053061.07468389180847.4636245452053571.57056627180968.189002134
#Sta/Elev= 30
       0 1836.73    31.1 1812.65    55.3 1796.88   113.9  1768.7   137.3 1761.22
   151.9 1750.16   190.9 1727.53   200.6  1711.8   205.4 1705.58  222.341690.871
   231.2 1689.28   245.8 1689.49   249.6 1690.91     320 1696.34     332 1695.29
   380.7    1696   400.2  1697.7   461.6    1699     482 1697.01   514.7 1700.38
   536.5 1699.31   555.6 1695.97     572 1699.38   599.8 1696.85   680.7 1699.85
     701 1698.83   781.9 1700.32   808.3 1702.51   825.7 1708.32   841.2 1710.01
#Mann= 5 ,-1 , 0
       0      .1       0  222.34    .045       0   249.6      .1       0
  496.58     .04       0  596.58      .1       0
#XS Ineff= 2 , 0
                          286.84         1697.81
Permanent Ineff=
       F       F
Bank Sta=222.34,249.6
XS Rating Curve= 0 ,0
Exp/Cntr(USF)=0,0
Exp/Cntr=0.3,0.1
LCMann Table=0

Chan Stop Cuts=-1
Use User Specified Reach Order=0
Composite Channel Slope=5